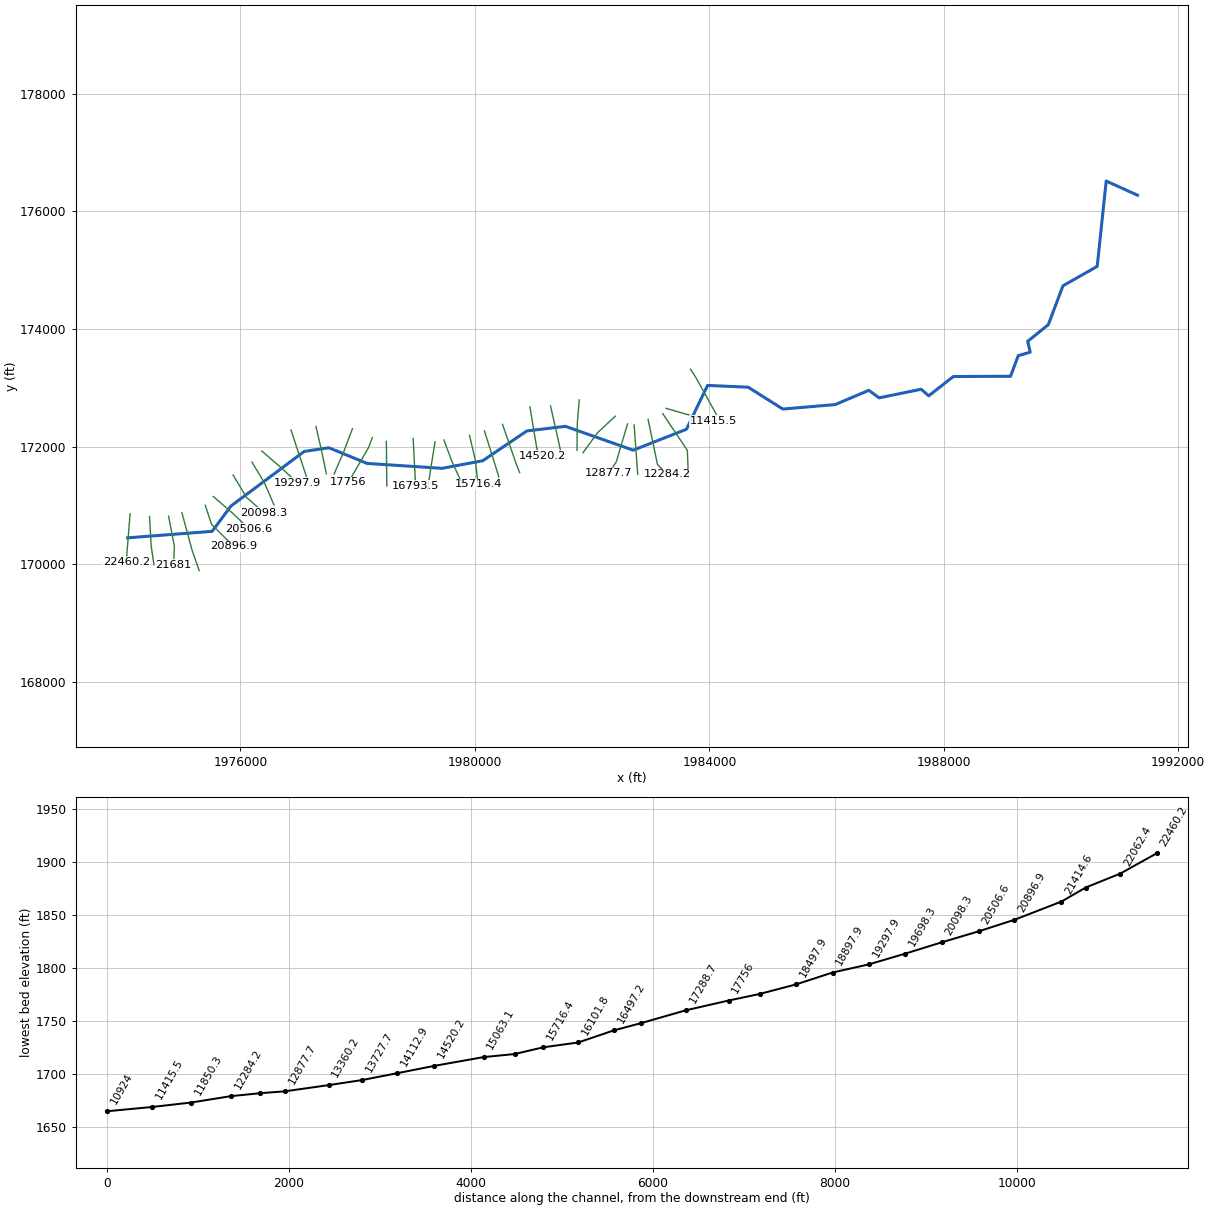
--- LckCrk.prj (project) ---

Proj Title=LckCrk
Current Plan=p01
Default Exp/Contr=0,0
English Units
Geom File=g01
Flow File=f01
Plan File=p01
BEGIN DESCRIPTION:
END DESCRIPTION:
DSS Export Rating Curves= 0
DSS Export Rating Curve Sorted= 0
DSS Export Volume Flow Curves= 0
DXF OffsetX= 0
DXF OffsetY= 0
DXF ScaleX= 0
DXF ScaleY= 0

--- LckCrk.p01 (plan) ---

Plan Title=Floodplain
Program Version=4.10
Short Identifier=Floodplain
Geom File=g01
Flow File=f01
Subcritical Flow
K Sum by GR= 0
Std Step Tol= 0.01
Critical Tol= 0.01
Num of Std Step Trials= 20
Max Error Tol= 0.3
Flow Tol Ratio= 0.001
Split Flow NTrial= 30
Split Flow Tol= 0.02
Split Flow Ratio= 0.02
Log Output Level= 0
Friction Slope Method= 1
Unsteady Friction Slope Method= 2
Unsteady Bridges Friction Slope Method= 1
Parabolic Critical Depth
Global Vel Dist= 0 , 0 , 0
Global Log Level= 0
CheckData=True
Encroach Param=-1 ,0,0, 0
Run HTab= 0
Run UNet= 0
Run PostProcess= 0
Run WQNet= 0
UNET Theta= 0
UNET Theta Warmup= 0
UNET ZTol= 0
UNET ZSATol= 0
UNET MxIter= 0
UNET MaxInSteps= 0
UNET DtIC= 0
UNET DtMin= 0
UNET MaxCRTS= 0
UNET WFStab= 0
UNET SFStab= 0
UNET WFX= 1
UNET SFX= 1
UNET DSS MLevel= 1
UNET DZMax Abort= 0
UNET Convert EG Bridges= 0
UNET Use Existing IB Tables= 0
UNET Froude Reduction=False
UNET Froude Limit= 0
UNET Froude Power= 0
UNET Time Slicing=0,0, 5
UNET Junction Losses=0
Write IC File= 0
Write IC File at Sim End=0
Echo Input=False
Echo Parameters=False
Echo Output=False
Write Detailed= 0
WQ AD Non Conservative
WQ ULTIMATE=-1
WQ Max Comp Step=1HOUR
WQ Output Interval=15MIN
WQ Output Selected Increments= 0
WQ Output face flow=0
WQ Output face velocity=0
WQ Output face area=0
WQ Output face dispersion=0
WQ Output cell volume=0
WQ Output cell surface area=0
WQ Output cell continuity=0
WQ Output cumulative cell continuity=0
WQ Output face conc=0
WQ Output face dconc_dx=0
WQ Output face courant=0
WQ Output face peclet=0
WQ Output face adv mass=0
WQ Output face disp mass=0
WQ Output cell mass=0
WQ Output cell source sink temp=0
WQ Output cell source sink nsm=0
WQ Output MaxMinRange=-1
WQ Daily Max Min Mean=-1
WQ Daily Range=0
WQ Daily Time=0
WQ Create Restart=0
WQ Fixed Restart=0
WQ System Summary=0
WQ Use Fixed Temperature=0
Sorting and Armoring Iterations= 10
XS Update Threshold= 0.02
Hydraulics Update Threshold= 0.02
Energy Slope Method= 1
Volume Change Method= 0
XS Weighting Method= 0
Number of US Weighted Cross Sections= 1
Number of DS Weighted Cross Sections= 1
Upstream XS Weight=0.25
Main XS Weight=0.5
Downstream XS Weight=0.25
Number of DS XS's Weighted with US Boundary= 1
Upstream Boundary Weight= 1
Weight of XSs Associated with US Boundary= 0
Number of US XS's Weighted with DS Boundary= 1
Downstream Boundary Weight= 0.5
Weight of XSs Associated with DS Boundary= 0.5
Sediment Output Level= 4
Mass or Volume Output= 0
Output Increment Type= 1
Profile and TS Output Increment= 10
XS Output Flag= 0
XS Output Increment= 10
Disregard all LS=0
Disregard all Conn=0
Disregard all Breaches=0
Disregard all Pumps=0

--- LckCrk.f01 (steady flow) ---

Flow Title=NFF Regression Equation
Program Version=4.00
Number of Profiles=1
Profile Names=P100yr
River Rch & RM=LckCrk,Main      ,22460.2
510.8924
River Rch & RM=LckCrk,Main      ,20896.9
523.3031
River Rch & RM=LckCrk,Main      ,20506.6
736.1474
River Rch & RM=LckCrk,Main      ,18097.9
923.6693
River Rch & RM=LckCrk,Main      ,18097.9
777.5205
River Rch & RM=LckCrk,Main      ,16793.5
952.1871
River Rch & RM=LckCrk,Main      ,14112.9
1055.583
River Rch & RM=LckCrk,Main      ,12284.2
1134.461
River Rch & RM=LckCrk,Main      ,11850.3
1504.552
River Rch & RM=LckCrk,Main      ,4599.6
1640.828
River Rch & RM=LckCrk,Main      ,4285.4
1848.414
River Rch & RM=LckCrk,Main      ,519
1902.374
River Rch & RM=LckCrk,Main      ,216.3
2510.080
Boundary for River Rch & Prof#=LckCrk,Main      ,1
Up Type=0
Dn Type=3
Dn Slope=0.006057

--- LckCrk.g01 (geometry) ---

Geom Title=USGS 3m DEM
Program Version=4.10

River Reach=LckCrk          ,Main
Reach XY= 30
     1974074.132      170450.348     1975517.303      170561.198
     1975837.995      170990.821     1977088.136      171919.376
     1977508.572       171981.35     1978161.053      171714.949
     1979439.698      171631.615     1980133.789      171760.744
     1980886.313      172267.032     1981545.167      172345.157
     1982700.565      171939.903     1983608.969      172295.678
     1983969.262      173040.704     1984662.797      173010.157
     1985253.166      172638.847      1986146.73      172714.949
     1986719.945      172957.408     1986895.428      172829.532
     1987611.574      172975.366     1987743.084      172864.688
     1988162.355      173191.511     1989138.917       173196.72
     1989269.126      173545.678     1989473.553      173605.574
     1989430.584       173790.47     1989782.146       174071.72
     1990032.146      174733.178     1990616.782      175063.907
     1990770.428      176514.428     1991303.815      176273.333

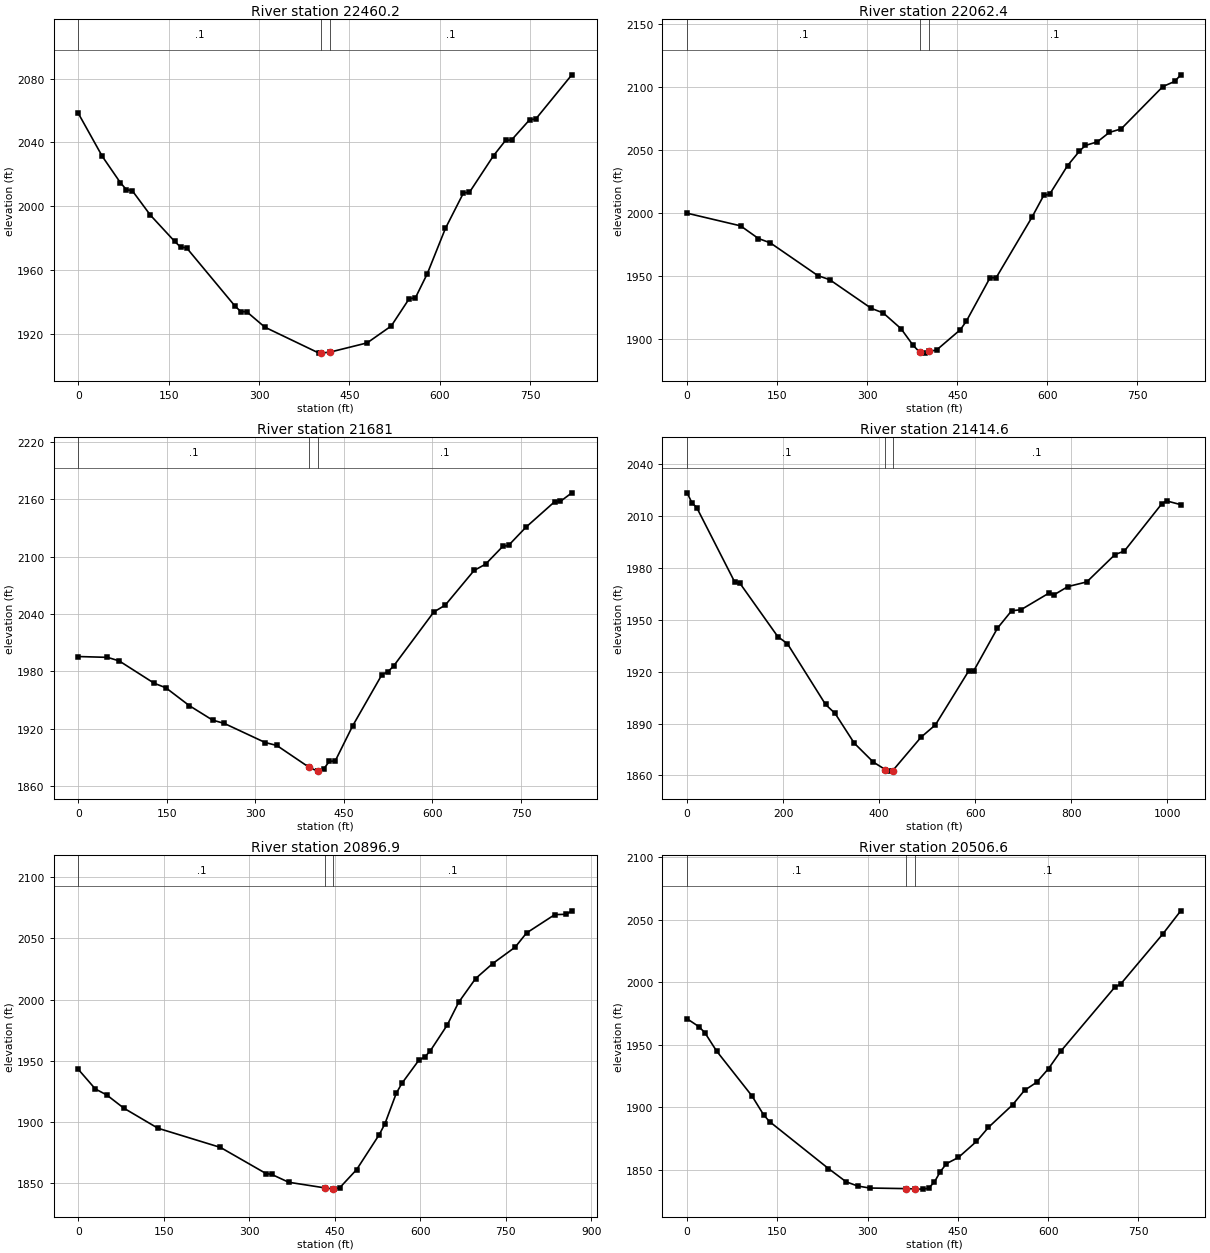
Type RM Length L Ch R = 1 ,22460.2 ,394.3,397.7,401.2
XS GIS Cut Line= 3
     1974117.158      170857.705     1974084.099      170449.541
     1974051.041      170041.378
#Sta/Elev= 30
       0 2058.37      40 2031.26    69.9 2014.82    79.9 2010.43    89.9 2009.66
   119.8 1994.42   159.8 1978.07   169.8 1974.42   179.8 1973.95   259.7 1937.63
   269.7    1934   279.7 1933.85   309.6 1924.23   399.5 1907.94     402 1908.02
     417  1908.5   479.4 1914.36   519.4 1924.96   549.3 1942.15   559.3 1942.47
   579.3 1957.82   609.3 1986.16   639.2 2008.36   649.2 2008.79   689.2 2031.79
   709.1 2041.31   719.1  2041.6   749.1 2054.29   759.1 2054.67     819 2082.41
#Mann= 3 , 0 , 0
       0      .1       0     402    .045       0     417      .1       0
Bank Sta=402,417
XS Rating Curve= 0 ,0
Exp/Cntr=0.3,0.1

Type RM Length L Ch R = 1 ,22062.4 ,378.3,381.4,384.5
XS GIS Cut Line= 3
     1974449.068      170813.189     1974475.813      170319.234
     1974523.983       169995.35
#Sta/Elev= 30
       0 1999.98      89 1989.95   118.7 1979.91   138.5 1976.45   217.7 1950.47
   237.4 1947.23   306.7 1924.49   326.5 1920.86   356.2 1908.36     376 1895.37
   387.3 1889.66   395.7 1888.95   402.3 1890.27   415.5 1891.43   455.1 1907.57
     465 1914.28   504.6 1948.88   514.5 1948.65   574.1 1996.61   593.9  2014.1
   603.8 2015.06   633.6 2037.76   653.4 2049.24   663.4 2053.77   683.2  2056.6
     703 2064.05   722.9 2066.89   792.4  2100.5   812.2  2104.6   822.1 2109.79
#Mann= 3 , 0 , 0
       0      .1       0   387.3    .045       0   402.3      .1       0
Bank Sta=387.3,402.3
XS Rating Curve= 0 ,0
Exp/Cntr=0.3,0.1

Type RM Length L Ch R = 1 ,21681   ,264.8,266.2,267.9
XS GIS Cut Line= 3
     1974773.908      170817.296     1974873.243      170302.441
     1974858.754      169991.054
#Sta/Elev= 30
       0 1995.54    49.5 1994.68    69.2 1991.03   128.6 1967.62   148.4 1962.89
     188 1944.28   227.6 1929.06   247.3 1925.64   316.6 1905.65   336.4 1902.56
   391.4 1879.59   405.6 1875.73   406.4 1875.89   415.5  1877.7   425.4 1886.01
   435.3 1886.31     465 1923.22   514.5 1976.67   524.4 1979.49   534.1  1985.5
   602.3 2042.08   621.8 2049.36   670.5  2085.5     690 2092.12   719.2 2110.73
   728.9 2111.71   758.1 2130.58   806.8 2157.31   816.6 2157.69   836.1  2166.7
#Mann= 3 , 0 , 0
       0      .1       0   391.4    .045       0   406.4      .1       0
Bank Sta=391.4,406.4
XS Rating Curve= 0 ,0
Exp/Cntr=0.3,0.1

Type RM Length L Ch R = 1 ,21414.6 ,504.9,517.6,530
XS GIS Cut Line= 3
     1975001.135      170875.784     1975173.648      170242.733
     1975296.795       169891.95
#Sta/Elev= 30
       0 2023.19     9.9 2017.45    19.9 2014.71    99.4 1971.51   109.4 1971.17
   188.9 1940.13   208.8  1936.1   288.3 1900.98   308.2 1895.79     348 1878.66
   387.7 1867.73     413 1863.36   417.5 1862.51     428 1862.76   487.1  1882.1
     517  1889.2   586.6 1920.47   596.5 1920.25   646.2 1945.03   675.7 1955.09
   695.3 1955.71     754 1965.38   763.8 1964.28   793.1 1969.08   832.2 1971.74
   890.9 1987.52   910.5 1989.57   988.8 2016.98   998.6 2018.51  1027.9 2016.37
#Mann= 3 , 0 , 0
       0      .1       0     413    .045       0     428      .1       0
Bank Sta=413,428
XS Rating Curve= 0 ,0
Exp/Cntr=0.3,0.1

Type RM Length L Ch R = 1 ,20896.9 ,388.8,390.3,391.9
XS GIS Cut Line= 3
     1975399.595      171003.622     1975505.772      170681.212
     1975879.526      170310.104
#Sta/Elev= 30
       0 1943.11      30 1927.04    49.9 1922.19    79.9 1911.41   139.8 1895.01
   249.6 1879.33   329.5 1858.02   339.4 1857.34   369.3 1850.91   432.7 1846.32
   447.7 1845.36   448.8  1845.3   458.7 1846.35   488.5 1861.23   528.3 1889.84
   538.2 1898.68   558.1 1923.56     568 1931.66   597.8 1950.57   607.8 1953.02
   617.7 1958.09   647.5 1979.22   667.4 1997.65   697.2  2017.1     727 2029.27
   766.8  2042.8   786.6 2054.31   836.3 2069.33   856.2 2069.55   866.1  2072.4
#Mann= 3 , 0 , 0
       0      .1       0   432.7    .045       0   447.7      .1       0
Bank Sta=432.7,447.7
XS Rating Curve= 0 ,0
Exp/Cntr=0.3,0.1

Type RM Length L Ch R = 1 ,20506.6 ,416.1,408.3,407.4
XS GIS Cut Line= 3
     1975535.424      171153.157     1975847.805      170886.076
     1976144.165      170603.658
#Sta/Elev= 30
       0 1970.64    19.6 1964.34    29.4 1959.56    48.9 1944.91   107.6 1909.08
   127.2 1893.84     137 1888.46   234.8 1850.96   264.2 1840.35   283.8 1836.92
   303.4 1835.37   364.4 1834.88   379.4 1834.61   391.4 1834.48   401.2  1835.1
     411 1840.22     421 1848.57     431 1854.84   450.9 1859.81   480.9  1872.6
   500.8 1883.85   540.8 1901.82   560.8 1913.48   580.7 1919.79   600.7 1930.82
   620.7 1944.53   710.5 1995.74   720.5 1998.38   790.4 2038.31   820.4 2056.95
#Mann= 3 , 0 , 0
       0      .1       0   364.4    .045       0   379.4      .1       0
Bank Sta=364.4,379.4
XS Rating Curve= 0 ,0
Exp/Cntr=0.3,0.1

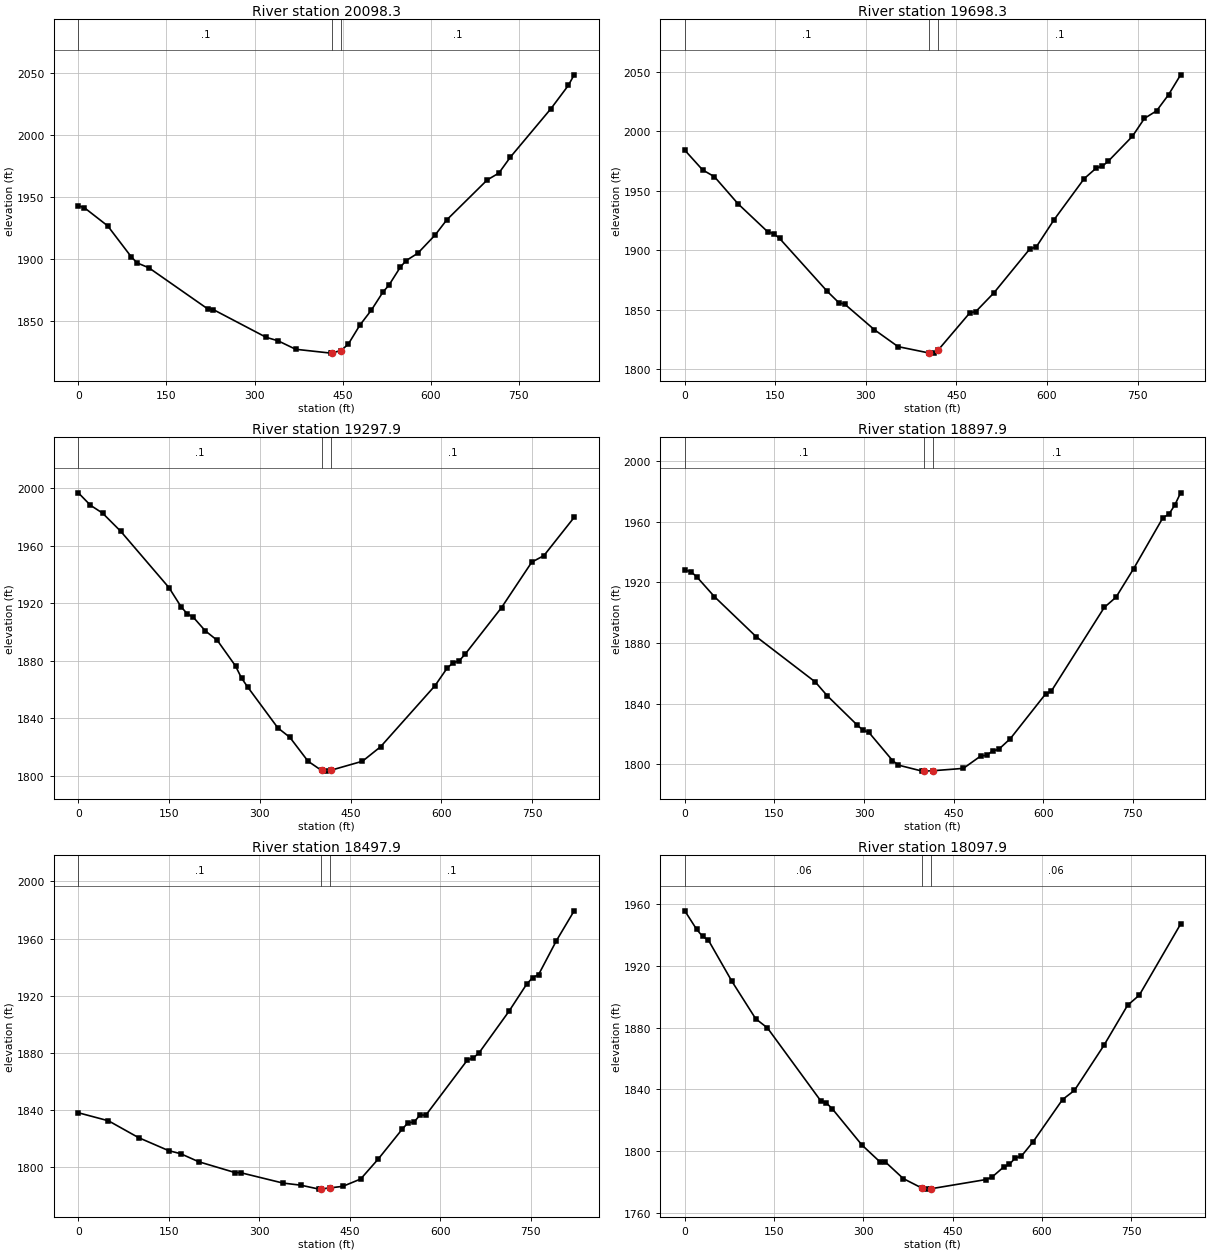
Type RM Length L Ch R = 1 ,20098.3 ,399.8,400,390
XS GIS Cut Line= 3
     1975874.778      171516.648     1976101.847       171139.95
     1976404.889      170872.557
#Sta/Elev= 30
       0 1942.72      10  1941.3      50 1926.57      90 1901.71     100 1896.76
     120 1892.83   219.9 1859.81   229.9 1859.11   319.9 1836.77   339.9 1834.02
   369.9 1827.18   429.8 1824.07   432.3  1824.3   447.3 1826.17   459.6 1831.38
   479.3 1846.66     499 1858.86   518.7 1873.38   528.6 1878.72   548.3 1893.48
   558.1 1898.65   577.8 1904.52   607.4 1919.25   627.1 1931.39   696.1 1963.63
   715.8 1969.09   735.6 1982.07   804.6 2021.07   834.1 2039.74     844 2048.26
#Mann= 3 , 0 , 0
       0      .1       0   432.3    .045       0   447.3      .1       0
Bank Sta=432.3,447.3
XS Rating Curve= 0 ,0
Exp/Cntr=0.3,0.1

Type RM Length L Ch R = 1 ,19698.3 ,392,400,410.3
XS GIS Cut Line= 3
     1976195.994      171737.731     1976409.071      171384.878
     1976572.295      171009.626
#Sta/Elev= 30
       0 1984.02    29.4 1967.49    49.1  1961.7    88.3 1938.89   137.4 1915.38
   147.2 1913.88     157 1909.86   235.5  1865.6   255.2 1855.81     265 1854.57
   314.1 1833.08   353.3 1818.86   404.7 1813.51   412.2  1813.4   419.7 1815.96
   472.1 1847.24   482.1 1848.33     512 1864.03   571.9 1901.23   581.9  1902.4
   611.8  1925.6   661.7 1960.13   681.7 1969.04   691.7 1970.55   701.6  1974.8
   741.6 1995.74   761.5 2010.79   781.5 2017.06   801.4 2030.64   821.4 2047.38
#Mann= 3 , 0 , 0
       0      .1       0   404.7    .045       0   419.7      .1       0
Bank Sta=404.7,419.7
XS Rating Curve= 0 ,0
Exp/Cntr=0.3,0.1

Type RM Length L Ch R = 1 ,19297.9 ,412.2,400,388.5
XS GIS Cut Line= 3
      1976364.28      171925.851     1976674.327      171658.392
     1976977.044      171382.335
#Sta/Elev= 30
       0 1996.92      20 1988.27      40 1982.81    69.9 1970.22   149.8 1930.93
   169.8 1917.63   179.8 1912.79   189.8 1910.42   209.7 1900.92   229.7 1894.21
   259.7 1876.45   269.6 1868.04   279.6 1861.91   329.6 1833.38   349.5 1826.78
   379.5 1810.18     402 1803.72   409.5 1803.28     417 1803.85   469.4 1810.16
   499.4 1820.25   589.3 1862.73   609.3 1874.93   619.3 1878.74   629.3 1880.03
   639.3 1884.78   699.2 1917.06   749.2 1948.72   769.2 1953.22   819.2 1979.85
#Mann= 3 , 0 , 0
       0      .1       0     402    .045       0     417      .1       0
Bank Sta=402,417
XS Rating Curve= 0 ,0
Exp/Cntr=0.3,0.1

Type RM Length L Ch R = 1 ,18897.9 ,402,400,397.3
XS GIS Cut Line= 3
     1976863.656      172280.964     1976990.272      171893.957
     1977124.693      171493.331
#Sta/Elev= 30
       0 1927.95     9.9 1927.06    19.9 1923.61    49.7 1910.45   119.2 1884.21
   218.5 1854.25   238.4 1845.21     288 1826.12     298 1822.57   307.9 1821.15
   347.6 1802.55   357.5 1799.51   397.3 1795.56   399.7 1795.56   414.7  1795.8
   466.2 1797.37   495.6 1805.62   505.5 1805.99   515.3 1808.94   525.1 1809.82
   544.8 1816.94   603.7 1846.34   613.6 1848.39     702 1903.38   721.7 1910.15
   751.2 1928.94   800.3 1962.58   810.1 1964.78   819.9 1970.72   829.8 1978.89
#Mann= 3 , 0 , 0
       0      .1       0   399.7    .045       0   414.7      .1       0
Bank Sta=399.7,414.7
XS Rating Curve= 0 ,0
Exp/Cntr=0.3,0.1

Type RM Length L Ch R = 1 ,18497.9 ,413.4,399.9,385.8
XS GIS Cut Line= 3
     1977287.914      172341.731     1977380.832      171943.225
     1977465.846      171538.942
#Sta/Elev= 30
       0 1837.91    49.9 1832.29    99.8  1820.5   149.7 1811.38   169.7 1809.22
   199.6 1803.59   259.5 1796.04   269.5 1795.88   339.3 1788.64   369.3 1787.13
   399.2 1784.39   401.7 1784.48   416.7 1785.22   438.7 1786.35   468.2 1791.47
   497.7 1805.64   537.1 1826.38   546.9 1830.98   556.7 1831.29   566.6 1836.34
   576.4 1836.26   645.3 1874.91   655.1 1876.35   664.9  1880.1   714.1 1908.97
   743.6 1928.09   753.5 1932.64   763.3 1934.73   792.8 1958.46   822.3 1979.44
#Mann= 3 , 0 , 0
       0      .1       0   401.7    .045       0   416.7      .1       0
Bank Sta=401.7,416.7
XS Rating Curve= 0 ,0
Exp/Cntr=0.3,0.1

Type RM Length L Ch R = 1 ,18097.9 ,345.7,341.9,339
XS GIS Cut Line= 3
     1977910.291      172304.919     1977766.359      171924.721
     1977597.208      171533.477
#Sta/Elev= 30
       0 1955.55    19.8 1943.61    29.8    1939    39.7 1936.51    79.3  1909.8
     119  1885.7   138.8 1879.73     228 1832.71     238  1831.1   247.9 1827.29
   297.5 1803.93   327.2 1793.23   337.1 1792.89   366.9 1782.22     399  1775.9
   406.5 1775.37     414 1775.65   505.7 1781.56   515.6 1783.03   535.4 1789.62
   545.3 1791.44   555.2 1795.63   565.1 1796.62     585 1806.01   634.5 1833.38
   654.4 1839.26   703.9  1868.4   743.6 1894.34   763.4 1900.96   832.8    1947
#Mann= 3 , 0 , 0
       0     .06       0     399    .045       0     414     .06       0
Bank Sta=399,414
XS Rating Curve= 0 ,0
Exp/Cntr=0.3,0.1

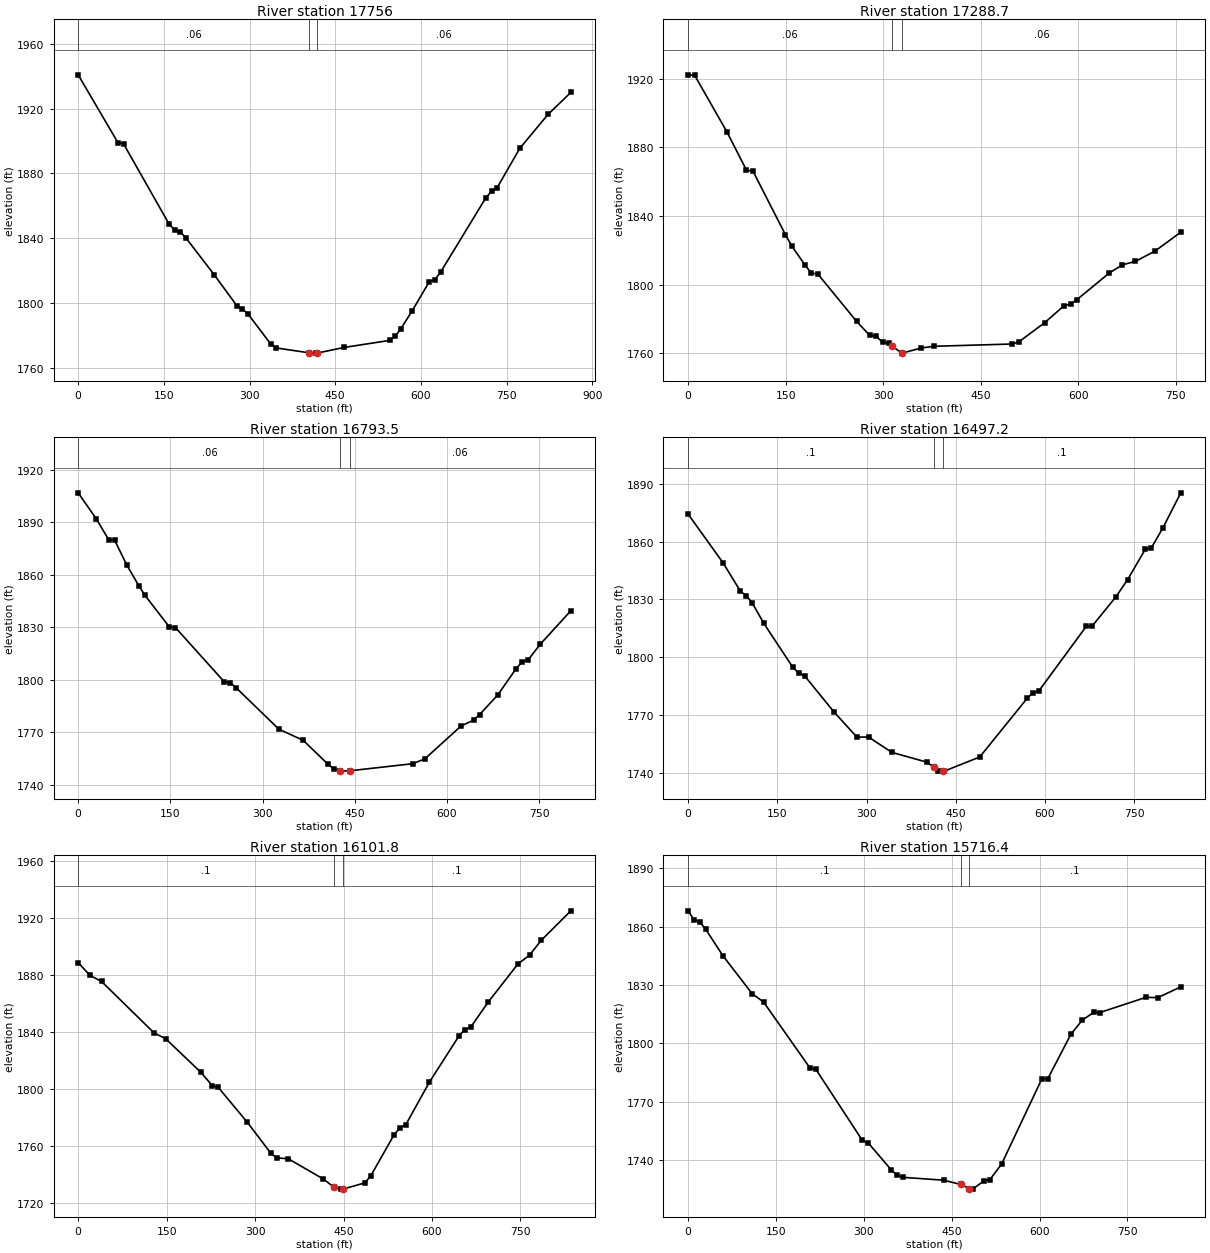
Type RM Length L Ch R = 1 ,17756   ,454.9,467.2,479.6
XS GIS Cut Line= 3
     1978249.395      172154.732     1978187.025       171987.32
     1977843.705       171395.84
#Sta/Elev= 30
       0 1940.85    69.5 1899.08    79.4 1898.33   158.8 1849.02   168.7 1845.12
   178.6 1844.01   188.6 1840.25   238.1 1817.56   277.8 1798.41   287.7 1796.27
   297.6  1793.2   337.2 1774.74   347.2 1772.34   403.6 1769.39   416.5 1769.16
   418.6 1769.21   466.1 1772.69   545.4 1777.01   555.3 1779.54   565.2 1784.34
     585 1795.34   614.8 1813.23   624.7 1814.57   634.6 1819.13   713.9 1865.05
   723.8 1868.96   733.7 1871.31   773.4 1895.57   822.9 1916.52   862.6 1929.98
#Mann= 3 , 0 , 0
       0     .06       0   403.6    .045       0   418.6     .06       0
Bank Sta=403.6,418.6
XS Rating Curve= 0 ,0
Exp/Cntr=0.3,0.1

Type RM Length L Ch R = 1 ,17288.7 ,494,495.1,496.1
XS GIS Cut Line= 2
     1978489.295      172089.943     1978496.759        171332.4
#Sta/Elev= 30
       0 1922.41      10 1922.15    59.8 1889.02    89.7 1866.76    99.7 1866.22
   149.5 1829.19   159.5 1822.44   179.4 1811.62   189.4 1806.71   199.4  1806.2
   259.2 1778.47   279.1  1770.4   289.1  1769.9     299  1766.3     309 1765.72
   313.8 1764.04   328.8    1760   358.8 1763.02   378.8    1764   498.4 1765.32
   508.4 1766.52   548.2 1777.74   578.2  1787.7   588.1 1788.52   598.1 1791.27
   647.9 1806.83   667.9 1811.53   687.8 1813.53   717.7 1819.48   757.6 1830.57
#Mann= 3 , 0 , 0
       0     .06       0   313.8    .045       0   328.8     .06       0
Bank Sta=313.8,328.8
XS Rating Curve= 0 ,0
Exp/Cntr=0.3,0.1

Type RM Length L Ch R = 1 ,16793.5 ,301.2,296.4,291.7
XS GIS Cut Line= 2
     1978946.433      172138.455     1978987.482      171337.998
#Sta/Elev= 30
       0 1906.95    29.7 1891.96    49.5 1880.21    59.4 1879.82    79.2 1865.59
      99 1853.64   108.8 1848.28   148.4 1830.24   158.3  1829.9   237.5 1798.95
   247.4  1798.3   257.3  1795.4   326.5 1771.82   366.1 1765.44   405.7 1752.04
   415.6 1749.19   425.5 1747.84   426.7 1747.85   441.7 1748.03   544.2 1752.08
     564 1754.84   623.4  1773.8   643.2 1776.92   653.1 1780.18   682.8 1791.46
   712.4 1806.39   722.4 1810.33   732.2 1811.53     752 1820.47   801.5 1839.53
#Mann= 3 , 0 , 0
       0     .06       0   426.7    .045       0   441.7     .06       0
Bank Sta=426.7,441.7
XS Rating Curve= 0 ,0
Exp/Cntr=0.3,0.1

Type RM Length L Ch R = 1 ,16497.2 ,381.6,395.3,408.8
XS GIS Cut Line= 3
     1979319.762      172079.715      1979252.27      171664.496
     1979190.959      171261.606
#Sta/Elev= 30
       0 1874.17    58.7 1848.97      88 1834.21    97.8 1831.91   107.6 1828.28
   127.2 1817.62   176.1 1794.81   185.9 1791.89   195.7 1790.47   244.6 1771.95
   283.7  1758.7   303.3 1758.74   342.4  1750.8   401.1 1745.74   413.2 1743.13
   420.7  1741.4   428.2 1741.16   430.6 1741.08   490.2 1748.39   569.8 1778.72
   579.7 1781.71   589.6  1782.6   669.2    1816   679.1 1816.15   718.9 1831.26
   738.7  1840.2   768.6    1856   778.5 1856.55   798.4 1867.22   828.2 1885.21
#Mann= 3 , 0 , 0
       0      .1       0   413.2    .045       0   428.2      .1       0
Bank Sta=413.2,428.2
XS Rating Curve= 0 ,0
Exp/Cntr=0.3,0.1

Type RM Length L Ch R = 1 ,16101.8 ,393.1,385.4,377.7
XS GIS Cut Line= 3
     1979471.134      172112.924     1979614.104      171733.063
     1979795.221      171343.512
#Sta/Elev= 30
       0 1888.48    19.8 1879.58    39.6 1875.25   128.7 1839.18   148.5 1835.03
   207.9 1811.59   227.7 1802.05   237.6 1800.92   287.1 1776.36   326.7 1754.75
   336.6 1751.51   356.4 1750.84   415.9 1736.64   434.1 1730.82   445.8 1729.57
   449.1 1729.61   485.8  1733.9   495.8 1738.59   535.8 1767.74   545.7 1772.59
   555.7 1774.81   595.7 1804.65   645.6 1836.88   655.6 1841.48   665.6 1843.11
   695.6  1860.9   745.6 1887.42   765.5 1893.76   785.5 1904.17   835.5  1924.8
#Mann= 3 , 0 , 0
       0      .1       0   434.1    .045       0   449.1      .1       0
Bank Sta=434.1,449.1
XS Rating Curve= 0 ,0
Exp/Cntr=0.3,0.1

Type RM Length L Ch R = 1 ,15716.4 ,307.9,312.2,316.6
XS GIS Cut Line= 3
     1979907.783      172190.967     1980007.573      171766.264
     1980052.839      171364.027
#Sta/Elev= 30
       0 1868.18     9.9 1863.64    19.8 1862.47    29.8 1858.76    59.5 1845.02
   109.1 1825.61   128.9 1821.21   208.2 1787.24   218.1 1786.63   297.5 1750.03
   307.4 1748.78     347 1734.82     357 1732.08   366.9 1731.07   436.3 1729.59
   465.3  1727.4   480.3 1725.26   485.6    1725   505.4 1729.32   515.2 1729.94
     535 1737.82   604.1 1781.89     614 1781.83   653.5 1804.72   673.2 1812.06
     693 1816.02   702.8 1815.84   781.8 1823.69   801.6  1823.5     841 1829.06
#Mann= 3 , 0 , 0
       0      .1       0   465.3    .045       0   480.3      .1       0
Bank Sta=465.3,480.3
XS Rating Curve= 0 ,0
Exp/Cntr=0.3,0.1

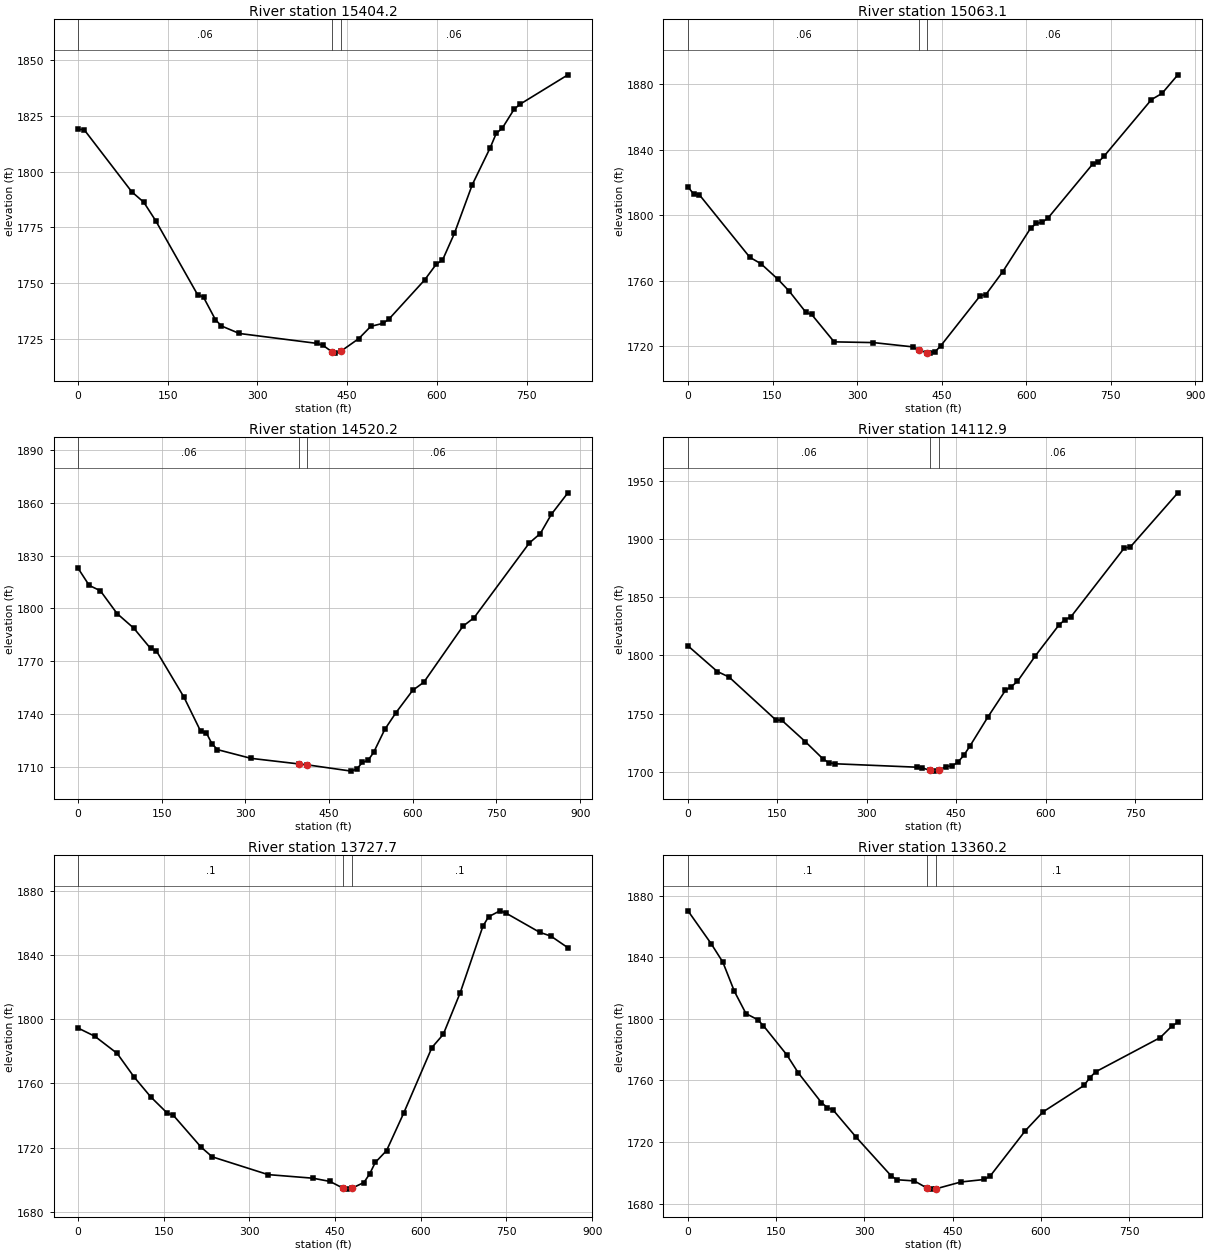
Type RM Length L Ch R = 1 ,15404.2 ,340.1,340.9,341.6
XS GIS Cut Line= 3
     1980161.902      172268.513      1980286.02      171878.265
     1980407.668      171487.253
#Sta/Elev= 30
       0  1818.9      10 1818.83    89.9 1790.92   109.9 1786.26   129.8    1778
   199.8 1744.89   209.8 1743.72   229.7 1733.67   239.7 1730.85   269.7 1727.48
   399.5 1723.04   409.5 1722.18   424.1 1719.36   429.5 1718.68   439.1 1719.47
   469.4 1725.19   489.4 1730.66   509.4 1731.99   519.4  1733.8   579.3  1751.4
   599.3 1758.65   609.3 1760.29   629.2 1772.29   659.2 1794.17   689.2 1810.72
   699.2 1817.11   709.1 1819.35   729.1 1827.92   739.1 1830.18     819 1843.32
#Mann= 3 , 0 , 0
       0     .06       0   424.1    .045       0   439.1     .06       0
Bank Sta=424.1,439.1
XS Rating Curve= 0 ,0
Exp/Cntr=0.3,0.1

Type RM Length L Ch R = 1 ,15063.1 ,547.9,542.8,537.5
XS GIS Cut Line= 3
      1980471.38       172378.47      1980713.41      171681.317
     1980763.788      171560.036
#Sta/Elev= 30
       0 1817.33      10 1813.02      20  1812.6   109.7 1774.35   129.6 1770.38
   159.6 1760.92   179.5 1753.72   209.4 1740.65   219.4 1739.44   259.3 1722.68
   329.1 1722.24   398.9 1719.62   409.7 1717.43   424.7 1716.14   428.8  1715.8
   438.8 1716.72   448.8 1720.39   518.6 1750.87   528.6 1751.56   558.5 1765.51
   608.3 1792.26   618.3 1795.02   628.3 1795.74   638.2 1798.04     718 1831.21
     728  1832.5     738 1835.95   822.4 1870.66   841.2 1874.46   869.3  1885.8
#Mann= 3 , 0 , 0
       0     .06       0   409.7    .045       0   424.7     .06       0
Bank Sta=409.7,424.7
XS Rating Curve= 0 ,0
Exp/Cntr=0.3,0.1

Type RM Length L Ch R = 1 ,14520.2 ,406.9,407.1,406.9
XS GIS Cut Line= 3
     1980938.814      172675.466     1981058.596        171955.6
     1981151.879      171840.338
#Sta/Elev= 30
       0 1822.87      20  1813.1      40 1810.04      70 1797.07     100 1788.74
     130 1777.24     140 1776.08   189.9 1749.53   219.9 1730.09   229.9  1729.3
   239.9 1723.14   249.9 1719.73   309.9 1714.78     396 1711.59     411 1711.08
   489.8 1707.51   499.8 1708.81   509.8 1712.47   519.8 1713.64   529.8 1718.15
   549.8 1731.23   569.8 1740.72   599.8 1753.43   619.8 1758.06   689.8 1789.86
   709.8  1794.7   808.8 1837.18   828.6 1842.58   848.4 1853.51     878 1865.71
#Mann= 3 , 0 , 0
       0     .06       0     396    .045       0     411     .06       0
Bank Sta=396,411
XS Rating Curve= 0 ,0
Exp/Cntr=0.3,0.1

Type RM Length L Ch R = 1 ,14112.9 ,390.2,385.2,379.8
XS GIS Cut Line= 3
     1981289.688      172692.948     1981381.527      172290.314
     1981469.858      171891.164
#Sta/Elev= 30
       0 1808.14    49.2 1786.13    68.8 1781.42   147.5  1744.5   157.3  1744.3
   196.6 1726.02   226.2 1711.25     236 1707.86   245.8 1706.94   383.5 1703.98
   393.3 1703.34   405.5 1701.34     413  1700.6   420.5  1701.3   432.9 1704.56
   442.9 1705.06   452.9 1708.33   462.8 1714.24   472.8 1721.97   502.7 1746.74
   532.6 1770.01   542.6 1773.25   552.6 1777.57   582.5 1799.41   622.4  1826.1
   632.3 1830.58   642.3    1833     732 1892.23     742    1893   821.8 1939.55
#Mann= 3 , 0 , 0
       0     .06       0   405.5    .045       0   420.5     .06       0
Bank Sta=405.5,420.5
XS Rating Curve= 0 ,0
Exp/Cntr=0.3,0.1

Type RM Length L Ch R = 1 ,13727.7 ,385.9,367.4,353.3
XS GIS Cut Line= 3
     1981779.792      172793.131     1981746.471      172393.269
     1981741.274       171937.04
#Sta/Elev= 30
       0 1794.46    29.4 1789.34    68.5 1778.66    97.9 1764.08   127.2 1751.61
   156.6 1741.33   166.4 1740.29   215.3 1720.32   234.9 1714.26   332.7 1703.19
   411.2 1700.95   440.9 1698.95   464.1 1694.72   470.7 1694.15   479.1 1694.67
   500.4 1698.26   510.4 1703.58   520.3 1710.76   540.1 1718.16   569.9 1741.36
   619.5 1782.34   639.3 1790.51     669 1816.46   708.7 1857.84   718.6 1863.74
   738.5 1867.45   748.4 1866.17   807.9 1854.12   827.8 1851.69   857.5 1844.46
#Mann= 3 , 0 , 0
       0      .1       0   464.1    .045       0   479.1      .1       0
Bank Sta=464.1,479.1
XS Rating Curve= 0 ,0
Exp/Cntr=0.3,0.1

Type RM Length L Ch R = 1 ,13360.2 ,470,482.4,490.5
XS GIS Cut Line= 3
     1982394.413      172517.483     1982090.971      172235.543
      1981844.34      171897.454
#Sta/Elev= 30
       0 1870.12    39.4 1848.77    59.2 1836.83    78.9 1817.81    98.6 1803.36
   118.4 1799.45   128.2 1795.51   167.7 1776.72   187.4 1764.94   226.8 1745.58
   236.7 1742.38   246.6  1740.8     286 1723.04   345.2 1698.06     355 1695.47
   384.6 1694.71   406.7 1689.98   414.2 1689.37   421.7  1689.6     464 1694.02
   503.9 1695.64   513.8 1697.94   573.6  1727.4   603.5 1739.53   673.3 1756.72
   683.2 1761.86   693.2  1765.6   802.8  1787.8   822.7 1795.31   832.7 1797.74
#Mann= 3 , 0 , 0
       0      .1       0   406.7    .045       0   421.7      .1       0
Bank Sta=406.7,421.7
XS Rating Curve= 0 ,0
Exp/Cntr=0.3,0.1

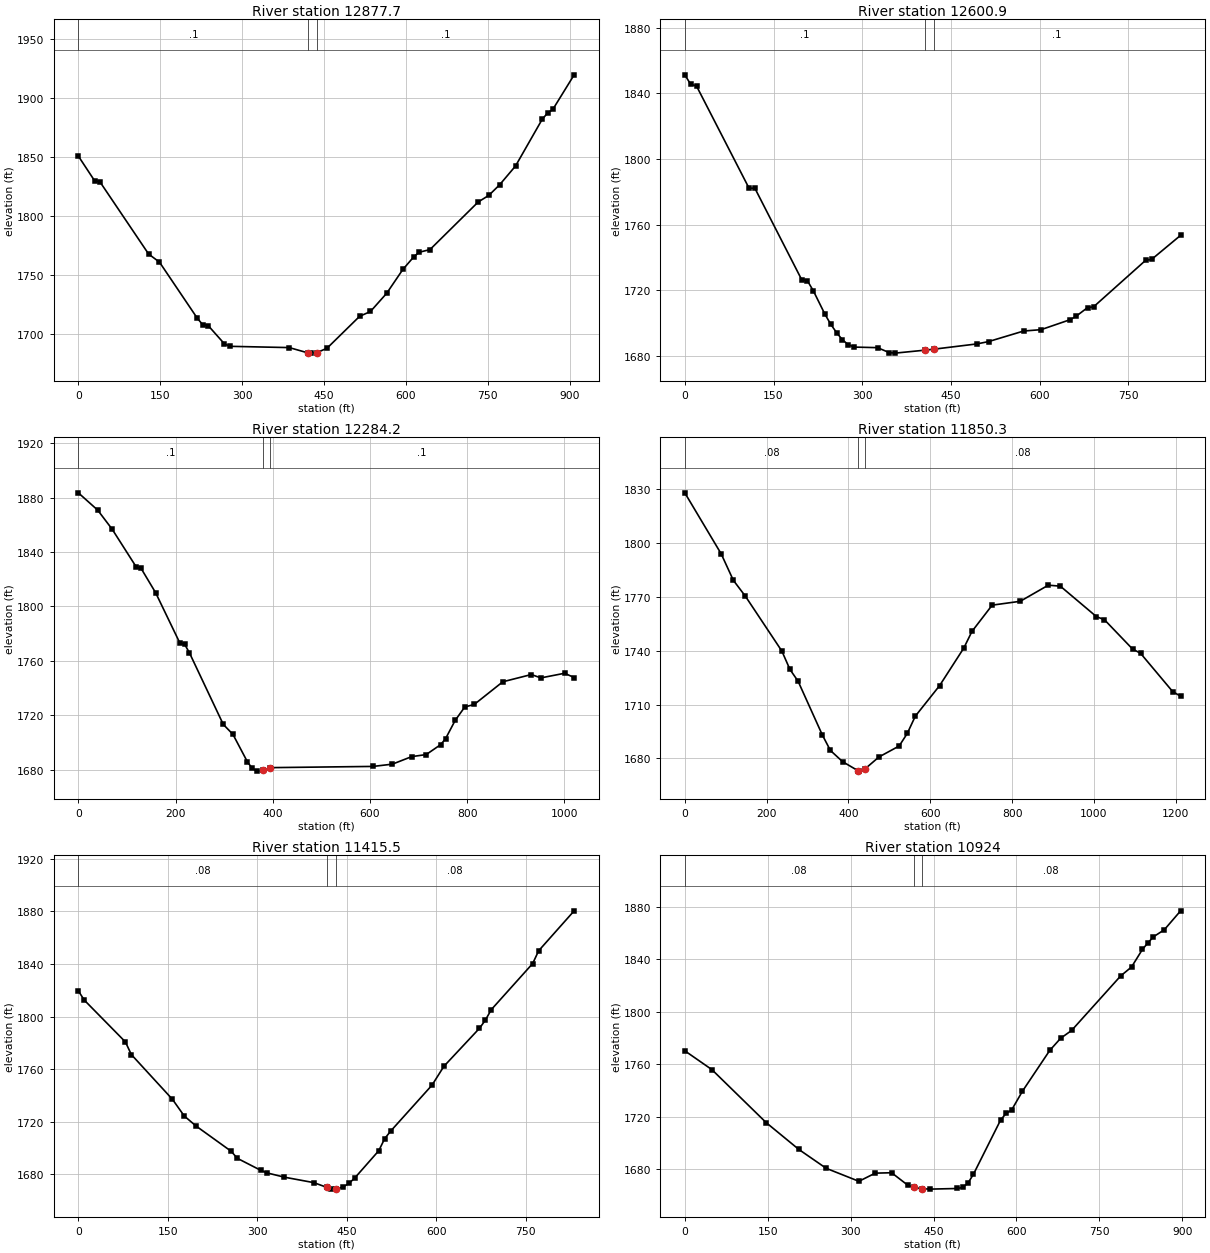
Type RM Length L Ch R = 1 ,12877.7 ,269,276.8,284.5
XS GIS Cut Line= 3
     1982603.786      172386.745      1982411.35      171741.025
     1982282.605      171545.109
#Sta/Elev= 30
       0 1850.51    29.7 1829.64    39.6 1828.64   128.8 1767.45   148.6 1760.63
     218 1713.02   227.9 1707.57   237.8 1706.88   267.5  1691.4   277.4 1689.28
   386.4  1688.2   421.3 1683.61   426.1 1683.51   436.3 1683.73   455.8 1687.78
   515.2 1714.69   535.1  1718.8   564.8 1734.21   594.5 1754.46   614.3 1765.04
   624.2 1768.98   644.1 1771.25   732.4 1811.58   751.9  1817.2   771.5 1826.07
   800.8 1842.08   849.6  1881.6   859.4 1886.92   869.1 1890.02   908.2 1919.34
#Mann= 3 , 0 , 0
       0      .1       0   421.3    .045       0   436.3      .1       0
Bank Sta=421.3,436.3
XS Rating Curve= 0 ,0
Exp/Cntr=0.3,0.1

Type RM Length L Ch R = 1 ,12600.9 ,312.9,316.6,320.4
XS GIS Cut Line= 3
     1982716.426      172367.665     1982762.133      171737.293
     1982777.351      171531.624
#Sta/Elev= 30
       0 1851.29     9.9 1845.54    19.8 1844.47   108.6 1782.21   118.5 1782.16
   197.5 1726.52   207.4 1725.71   217.3 1719.68     237 1705.33   246.9  1699.2
   256.8 1694.06   266.6 1689.79   276.5 1686.79   286.4 1685.37   325.9 1685.01
   345.6    1682   355.5 1681.68   405.6 1683.47   420.6 1684.06   493.8 1687.29
   513.5 1688.71   572.8 1695.14   602.4 1695.99   651.7 1702.09   661.5 1704.13
   681.1 1709.47     691 1709.85   779.3 1738.29   789.2 1738.78   838.3 1753.48
#Mann= 3 , 0 , 0
       0      .1       0   405.6    .045       0   420.6      .1       0
Bank Sta=405.6,420.6
XS Rating Curve= 0 ,0
Exp/Cntr=0.3,0.1

Type RM Length L Ch R = 1 ,12284.2 ,424.9,433.9,442.9
XS GIS Cut Line= 3
     1982954.317      172464.982     1983114.782      171696.244
      1983282.71      171532.048
#Sta/Elev= 30
       0 1883.56    39.8 1870.86    69.6 1856.81   119.3 1828.97   129.2 1827.97
     159 1810.15   208.8 1773.22   218.7 1772.24   228.6 1765.93   298.2 1713.32
   318.1 1705.99   347.9 1685.79   357.9 1680.93   367.8 1678.96   379.4 1679.48
   394.4 1681.52   606.4 1682.42   646.1 1684.08   685.9 1689.62   715.7 1691.12
   745.5 1698.43   755.5 1702.75   775.4 1716.25   795.1  1726.1   814.7    1728
   873.4 1744.65   932.1 1749.97   951.7  1747.5  1000.6 1750.91  1020.2 1747.76
#Mann= 3 , 0 , 0
       0      .1       0   379.4    .045       0   394.4      .1       0
Bank Sta=379.4,394.4
XS Rating Curve= 0 ,0
Exp/Cntr=0.3,0.1

Type RM Length L Ch R = 1 ,11850.3 ,418.7,434.8,452.1
XS GIS Cut Line= 3
     1983204.952      172559.812     1983624.475       171936.63
      1983641.89      171476.383
#Sta/Elev= 30
       0 1828.11      89 1794.06   118.6 1779.36   148.3  1770.4   237.2  1739.9
     257 1729.63   276.8 1723.12   336.1 1693.14   355.8  1684.5   385.5 1678.26
   424.4 1673.05     425 1672.96   439.4    1674   474.5 1680.85   523.9 1686.97
   543.7 1693.97   563.4  1703.6   622.7 1720.62     682 1741.62   701.8 1750.84
   751.2 1765.49   819.8 1767.64   888.4 1776.62   917.8 1776.08    1006 1759.09
  1025.6 1757.36  1094.2 1741.05  1113.8 1738.66  1192.2 1717.35  1211.8  1714.7
#Mann= 3 , 0 , 0
       0     .08       0   424.4    .045       0   439.4     .08       0
Bank Sta=424.4,439.4
XS Rating Curve= 0 ,0
Exp/Cntr=0.3,0.1

Type RM Length L Ch R = 1 ,11415.5 ,509.4,491.3,472.1
XS GIS Cut Line= 3
     1983263.699      172651.045     1983670.918      172532.628
     1984066.932      172439.024
#Sta/Elev= 30
       0 1819.61     9.9 1812.58    78.9 1780.73    88.8 1771.14   157.8 1737.01
   177.5 1724.38   197.2 1716.77   256.4 1697.44   266.3  1692.2   305.7 1683.03
   315.6 1681.14   345.2 1677.82   394.5 1673.67   416.6 1670.04   424.1 1668.71
   431.6 1668.71   443.9 1670.37   453.9 1673.18   463.8 1677.46   503.5 1697.93
   513.4  1707.1   523.3 1712.78   592.8 1747.86   612.7 1762.18   672.2 1791.05
   682.1 1797.23   692.1 1805.31   761.5 1840.41   771.5 1850.11     831  1880.5
#Mann= 3 , 0 , 0
       0     .08       0   416.6    .045       0   431.6     .08       0
Bank Sta=416.6,431.6
XS Rating Curve= 0 ,0
Exp/Cntr=0.3,0.1

Type RM Length L Ch R = 1 ,10924   ,388,374.4,360.3
XS GIS Cut Line= 3
     1983676.719      173317.373     1983768.769      173178.055
     1984123.458      172539.828
#Sta/Elev= 30
       0 1770.19    49.1 1755.81   147.3 1715.41   206.4 1694.96   255.8  1680.6
     315 1670.69   344.6 1676.91   374.2 1677.21   403.8  1667.6     414 1666.07
     429 1665.06   443.3 1664.72   492.6  1665.2   502.5 1665.99   512.3  1669.3
   522.2 1676.03   571.5  1717.5   581.4 1722.48   591.3 1725.04     611 1739.45
   660.3 1770.47   680.1 1779.77   699.8 1785.68   788.6 1827.26   808.3  1834.1
   828.1 1847.57   837.9 1852.44   847.8 1857.08   867.5 1862.45   897.1 1876.91
#Mann= 3 , 0 , 0
       0     .08       0     414    .045       0     429     .08       0
Bank Sta=414,429
XS Rating Curve= 0 ,0
Exp/Cntr=0.3,0.1