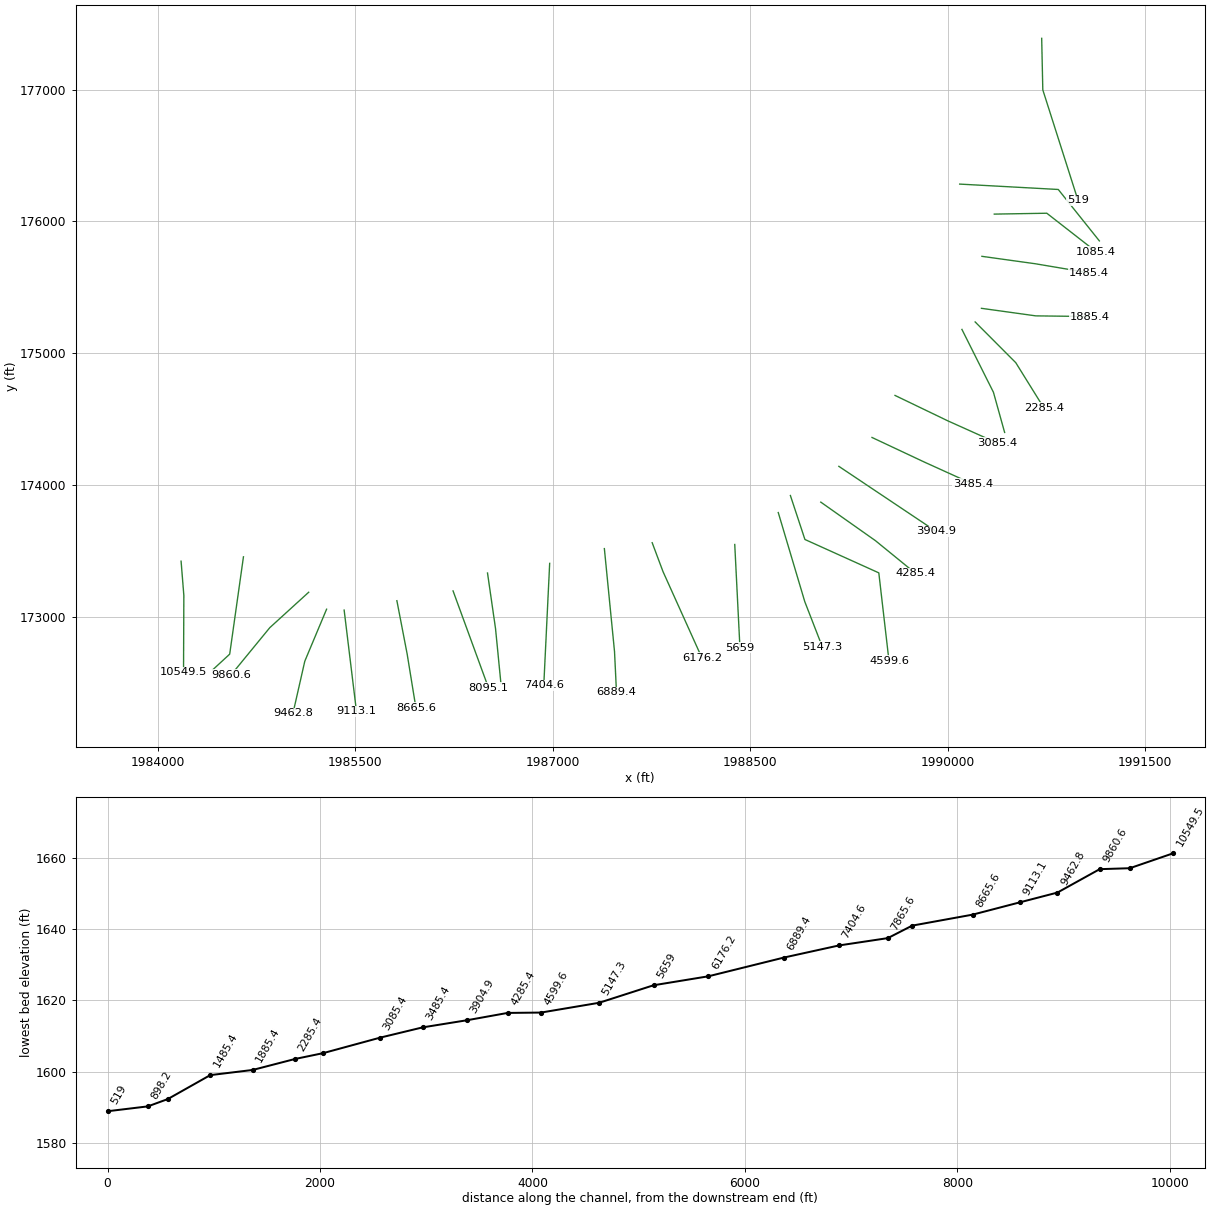
HEC-RAS study LckCrk.prj: LckCrk

--- LckCrk.g01 (geometry) --- (continued)

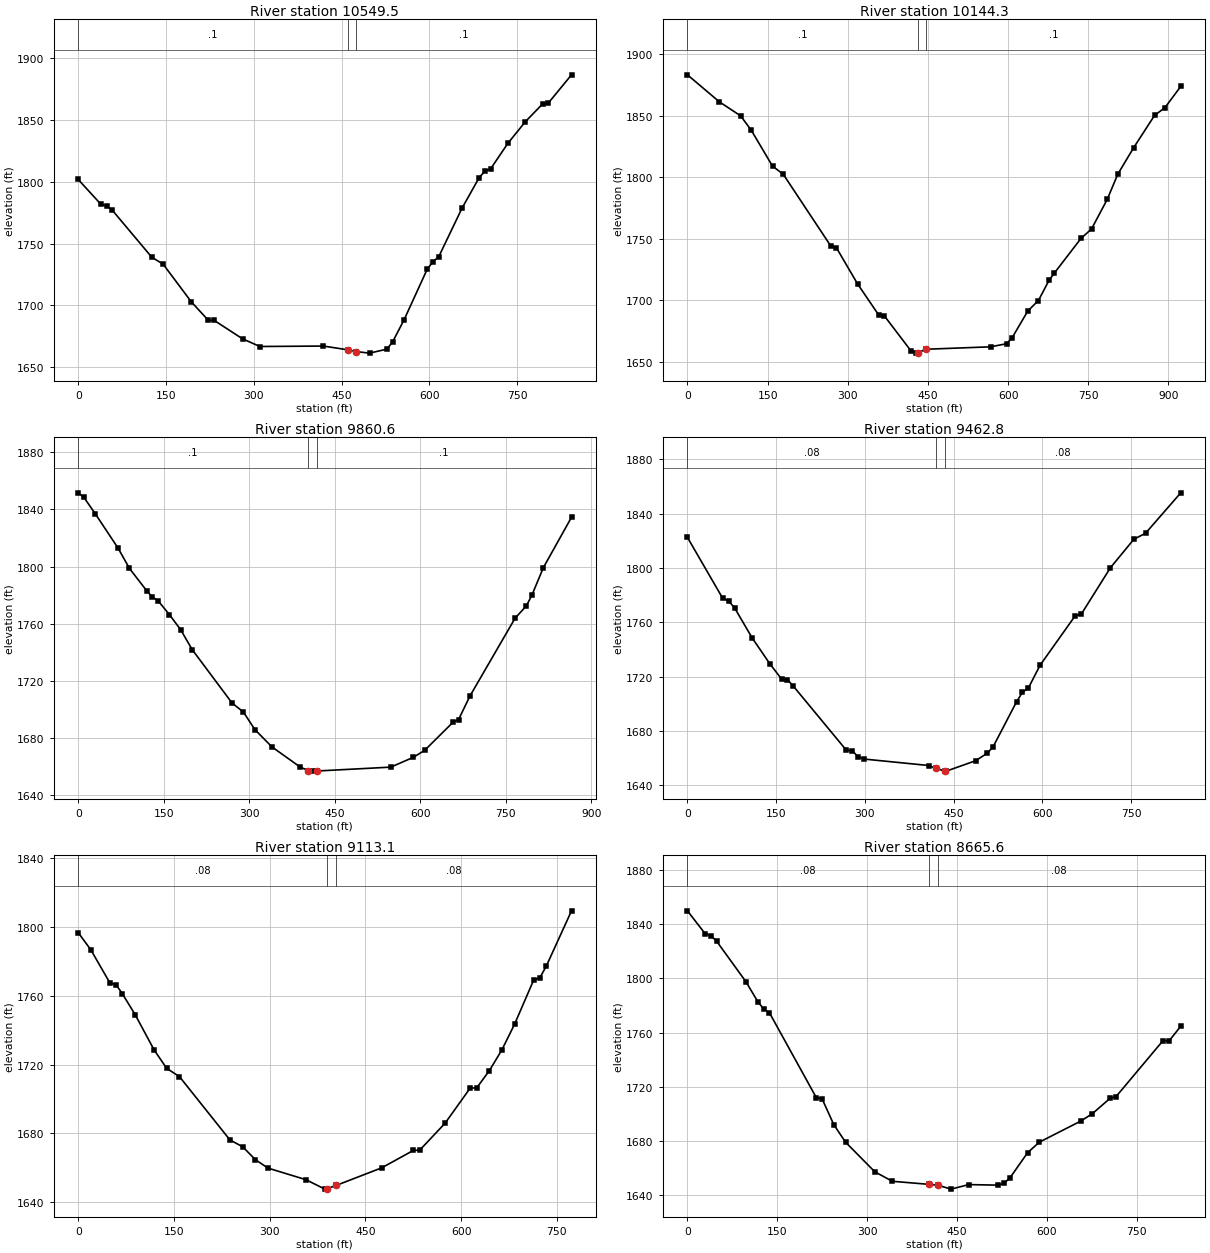
Type RM Length L Ch R = 1 ,10549.5 ,408.8,405.2,401.6
XS GIS Cut Line= 3
     1984175.685       173420.99     1984196.675       173160.64
     1984194.274      172578.784
#Sta/Elev= 30
       0 1801.94    38.7 1781.95    48.4 1780.48      58 1777.23   125.8 1739.01
   145.1 1733.46   193.5 1702.82   222.5 1687.93   232.2 1687.97   280.9    1673
   310.5 1666.79     419 1667.16   460.3 1664.15   475.3 1662.65   497.9 1661.43
   527.5 1664.64   537.3 1670.47   557.1 1688.56   596.5 1729.36   606.4 1735.42
   616.2 1739.45   655.7 1778.48   685.3 1803.47   695.1 1808.74     705 1810.68
   734.6 1831.39   764.2 1848.69   793.8 1863.15   803.6 1863.88   843.1 1886.64
#Mann= 3 , 0 , 0
       0      .1       0   460.3    .045       0   475.3      .1       0
Bank Sta=460.3,475.3
XS Rating Curve= 0 ,0
Exp/Cntr=0.3,0.1

Type RM Length L Ch R = 1 ,10144.3 ,297.6,283.6,271.3
XS GIS Cut Line= 3
     1984649.459      173454.203      1984544.97      172715.319
     1984414.923      172595.535
#Sta/Elev= 30
       0 1883.24    59.7 1861.32    99.5 1849.93   119.4 1838.24   159.2 1809.08
   179.1 1802.59   268.6 1743.99   278.6 1742.91   318.4 1713.41   358.2 1687.99
   368.1  1687.7   417.9 1659.29   427.8 1657.26   431.5 1657.68   446.5 1660.42
   567.1 1662.38     597 1664.87   606.9 1669.31   636.8 1691.47   656.7 1699.98
   676.6 1716.43   686.5 1722.25   736.3  1750.4   756.1 1758.11   785.5 1782.15
   805.2 1802.56   834.6 1823.89   873.9 1850.23   893.6 1856.68     923 1873.84
#Mann= 3 , 0 , 0
       0      .1       0   431.5    .045       0   446.5      .1       0
Bank Sta=431.5,446.5
XS Rating Curve= 0 ,0
Exp/Cntr=0.3,0.1

Type RM Length L Ch R = 1 ,9860.6  ,389.7,397.7,408.1
XS GIS Cut Line= 3
     1985145.063       173185.24     1984849.495      172916.251
     1984554.317      172556.507
#Sta/Elev= 30
       0 1851.61      10 1848.42      30 1836.94    69.9 1812.93    89.9 1798.72
   119.9 1783.23   129.9 1778.75   139.9  1776.2   159.9 1766.46   179.8 1755.81
   199.8 1742.02   269.8 1704.61   289.7 1698.32   309.7 1686.08   339.7 1673.94
   389.6 1659.74   403.3 1657.39   409.6 1656.99   418.3 1657.07   548.2 1659.79
   587.8 1666.68   607.6 1671.55   657.1 1691.13     667 1693.07   686.8 1709.43
     766  1763.9   785.8 1772.56   795.7 1780.18   815.5 1799.18     865 1834.52
#Mann= 3 , 0 , 0
       0      .1       0   403.3    .045       0   418.3      .1       0
Bank Sta=403.3,418.3
XS Rating Curve= 0 ,0
Exp/Cntr=0.3,0.1

Type RM Length L Ch R = 1 ,9462.8  ,338,349.7,357.5
XS GIS Cut Line= 3
      1985280.93      173056.432     1985115.444      172661.927
     1985025.407       172265.76
#Sta/Elev= 30
       0 1822.51    59.7 1777.62    69.6 1775.69    79.6 1770.71   109.4 1748.52
   139.3 1729.46   159.2 1718.18   169.1 1717.75   179.1 1712.96   268.6 1665.82
   278.6 1665.43   288.5 1661.01   298.5  1659.3   407.9 1654.54   420.3 1652.34
   435.3 1650.51   437.7  1650.4   487.3 1658.06   507.1 1663.65     517 1668.47
   556.6 1701.58   566.5 1708.49   576.4 1711.57   596.3 1728.43   655.7 1764.85
   665.6 1765.79   715.2  1800.2   754.8 1821.15   774.6  1825.6   834.1 1855.36
#Mann= 3 , 0 , 0
       0     .08       0   420.3    .045       0   435.3     .08       0
Bank Sta=420.3,435.3
XS Rating Curve= 0 ,0
Exp/Cntr=0.3,0.1

Type RM Length L Ch R = 1 ,9113.1  ,445.8,447.4,448.3
XS GIS Cut Line= 2
     1985414.291      173049.742     1985507.758      172282.438
#Sta/Elev= 30
       0 1796.59    19.8  1786.6    49.6 1767.42    59.5 1766.26    69.4 1760.95
    89.2 1748.99   118.9 1728.52   138.7 1717.77   158.6 1713.01   237.8 1676.21
   257.7 1672.28   277.5 1664.83   297.3  1659.9   356.8 1653.17   386.5 1647.68
   389.5 1647.86   404.5 1649.87   475.7 1660.06   525.2 1670.16   535.1 1670.28
   574.8  1685.9   614.4 1706.42   624.3 1706.38   644.2 1716.42     664 1728.57
   683.8 1743.43   713.5 1768.88   723.4 1770.42   733.3 1776.99     773 1809.23
#Mann= 3 , 0 , 0
       0     .08       0   389.5    .045       0   404.5     .08       0
Bank Sta=389.5,404.5
XS Rating Curve= 0 ,0
Exp/Cntr=0.3,0.1

Type RM Length L Ch R = 1 ,8665.6  ,567.8,570.4,573.6
XS GIS Cut Line= 3
     1985814.948      173121.013      1985892.72      172717.773
     1985959.121      172310.048
#Sta/Elev= 30
       0    1850    29.3 1833.22    39.1 1831.68    48.9 1827.43    97.8 1797.49
   117.3 1782.94   127.1 1777.51   136.9 1774.64   215.1 1711.92   224.9 1710.92
   244.4 1691.89     264 1678.92   312.9 1657.01   342.2 1649.99   403.2 1647.73
   418.2 1647.09   440.2 1644.19   469.7 1647.54   518.9 1647.14   528.7 1648.56
   538.5 1652.45     568  1671.1   587.7 1678.94   656.6 1694.45   676.2    1700
   705.7 1711.31   715.6 1712.54   794.3 1754.08   804.1 1753.67   823.8 1764.65
#Mann= 3 , 0 , 0
       0     .08       0   403.2    .045       0   418.2     .08       0
Bank Sta=403.2,418.2
XS Rating Curve= 0 ,0
Exp/Cntr=0.3,0.1

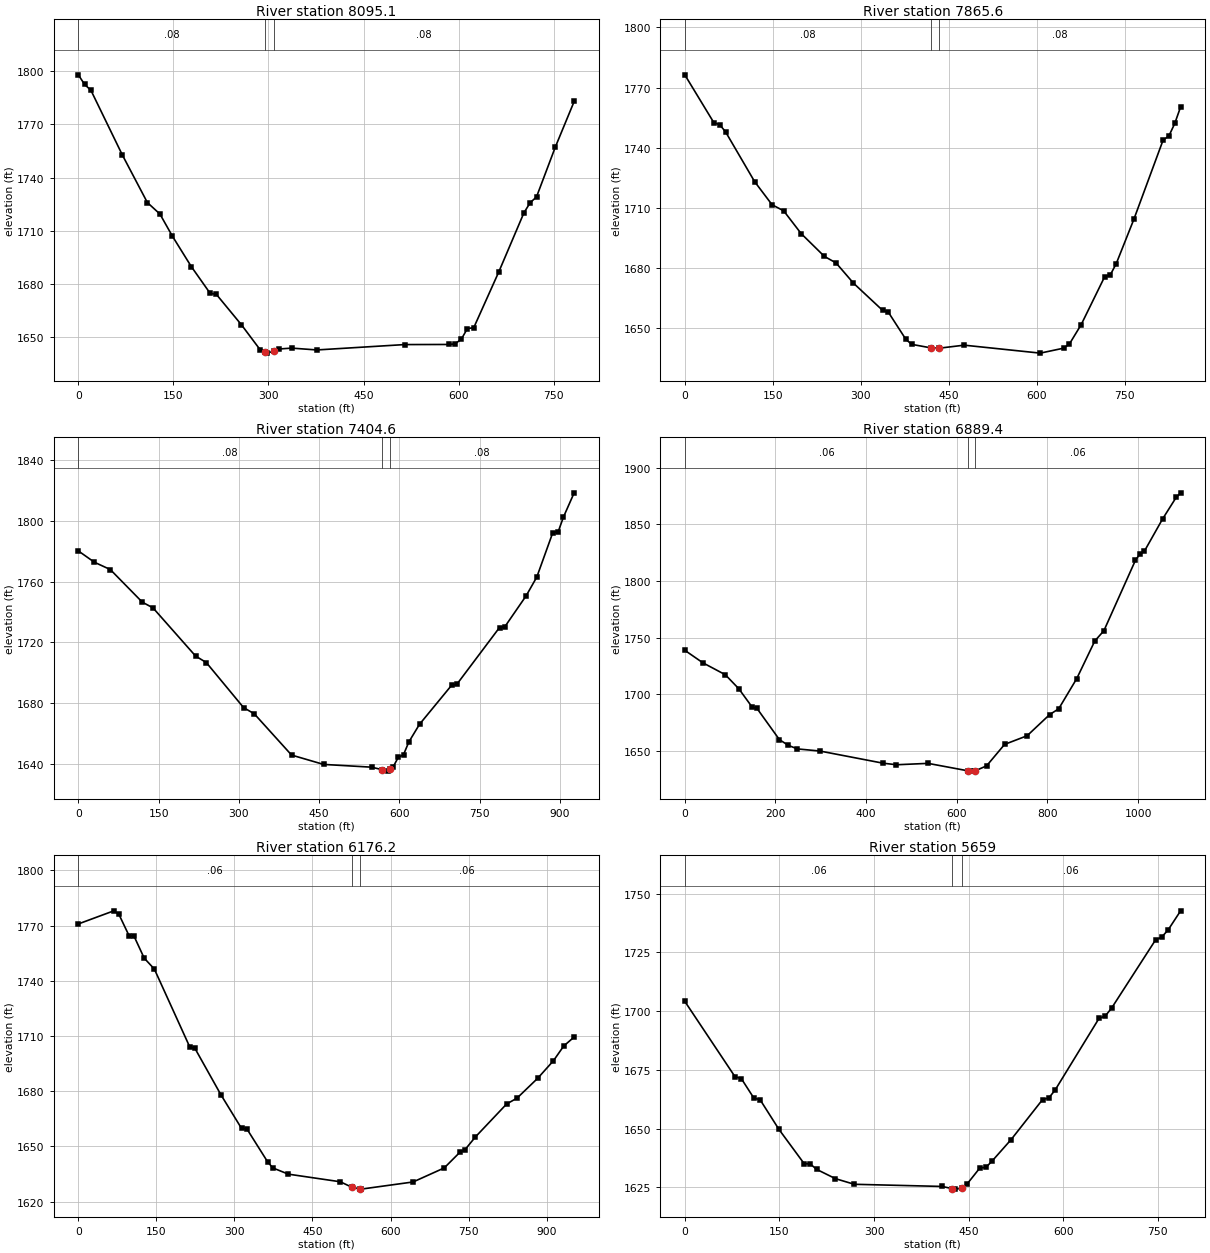
Type RM Length L Ch R = 1 ,8095.1  ,238.1,229.4,221.2
XS GIS Cut Line= 2
     1986241.666      173195.469     1986510.296      172460.888
#Sta/Elev= 30
       0 1797.92     9.9 1792.49    19.8 1789.24    69.3 1752.85   108.9 1725.95
   128.7 1719.48   148.5 1706.94   178.2 1689.87   207.9 1674.82   217.8 1674.18
   257.4 1657.02   287.1 1642.87   293.8 1641.67     297 1641.09   308.8 1642.17
   316.8 1643.42   336.6 1643.92   376.2 1642.88   514.8 1645.91   584.1 1645.97
     594 1646.26     604 1648.84   613.8 1654.94   623.8 1655.42   663.4 1686.95
     703  1720.2   712.8 1725.85   722.8 1729.12   752.5 1757.23   782.2 1782.92
#Mann= 3 , 0 , 0
       0     .08       0   293.8    .045       0   308.8     .08       0
Bank Sta=293.8,308.8
XS Rating Curve= 0 ,0
Exp/Cntr=0.3,0.1

Type RM Length L Ch R = 1 ,7865.6  ,462,461,461.5
XS GIS Cut Line= 3
     1986503.436      173331.128     1986564.331      172909.019
     1986605.348      172492.228
#Sta/Elev= 30
       0 1776.36    49.6 1752.47    59.5  1751.5    69.4 1747.97     119 1723.12
   148.8 1711.56   168.6 1708.53   198.4 1697.18     238 1685.81   257.9 1682.54
   287.6 1672.45   337.2 1658.91   347.1 1657.94   376.9 1644.43   386.8 1641.95
     419 1640.22     434 1640.04   476.3 1641.54     606 1637.57   645.8 1640.04
   655.8 1642.17   675.8  1651.8   715.6 1675.56   725.6 1676.68   735.6 1682.24
   765.5 1704.25   815.4 1743.79   825.3 1745.87   835.3  1752.1   845.3 1760.39
#Mann= 3 , 0 , 0
       0     .08       0     419    .045       0     434     .08       0
Bank Sta=419,434
XS Rating Curve= 0 ,0
Exp/Cntr=0.3,0.1

Type RM Length L Ch R = 1 ,7404.6  ,511.7,515.1,518.5
XS GIS Cut Line= 2
     1986975.574      173404.447     1986930.793      172478.976
#Sta/Elev= 30
       0 1780.16    29.9 1772.74    59.8  1767.9   119.6 1746.48   139.5 1742.75
   219.2 1711.06   239.1 1706.85   308.8 1677.24   328.8 1673.15   398.5 1646.05
   458.3 1639.91     548  1638.1   567.8 1636.44   577.8  1635.5   582.8 1636.74
   587.8 1637.97   597.8 1644.48   607.7 1646.33   617.7 1654.69   637.6 1666.26
   697.4 1691.82   707.4 1692.56   787.1 1729.83     797 1730.32   836.9 1750.68
   856.8 1762.99   886.7 1792.21   896.7 1792.71   906.6 1802.41   926.6 1818.31
#Mann= 3 , 0 , 0
       0     .08       0   567.8    .045       0   582.8     .08       0
Bank Sta=567.8,582.8
XS Rating Curve= 0 ,0
Exp/Cntr=0.3,0.1

Type RM Length L Ch R = 1 ,6889.4  ,704.7,712.9,721
XS GIS Cut Line= 3
     1987391.041      173516.399     1987468.163      172735.222
      1987483.09      172426.732
#Sta/Elev= 30
       0 1738.82    39.8  1727.8    89.4 1717.24   119.2 1704.84     149 1688.42
     159 1687.64   208.7 1659.94   228.5 1654.84   248.4 1651.73   298.1 1649.85
   437.2 1639.13     467 1637.74   536.6 1638.96   624.4  1632.4   635.9 1632.11
   639.4 1632.18   665.7 1636.75   705.5 1655.72   755.2 1663.36   804.9 1682.06
   824.8 1687.14   864.7 1713.89   904.5 1747.07   924.5  1756.1   994.2 1818.38
  1004.2 1823.96  1014.1  1826.5    1054 1854.82  1083.9 1873.81  1093.8 1877.89
#Mann= 3 , 0 , 0
       0     .06       0   624.4    .045       0   639.4     .06       0
Bank Sta=624.4,639.4
XS Rating Curve= 0 ,0
Exp/Cntr=0.3,0.1

Type RM Length L Ch R = 1 ,6176.2  ,526.2,516.9,507.5
XS GIS Cut Line= 3
     1987754.263      173561.179     1987836.361      173342.251
     1988132.172      172686.705
#Sta/Elev= 30
       0 1770.94    68.2 1778.07    77.9 1776.21    97.4 1764.61   107.2 1764.21
   126.6 1752.36   146.1 1746.43   214.3 1704.01   224.1 1703.33   273.8 1678.22
   313.7  1659.8   323.7 1659.66   363.7 1641.71   373.7 1638.36   403.6 1634.96
   503.5 1630.82   526.2 1627.79   541.2 1626.98   543.5 1626.82   643.4 1630.71
   703.3 1638.34   733.3 1646.83   743.2 1648.26   763.2 1655.18   823.2  1673.1
   843.1 1676.25   883.1 1687.12   913.1 1696.57     933 1704.62     953 1709.48
#Mann= 3 , 0 , 0
       0     .06       0   526.2    .045       0   541.2     .06       0
Bank Sta=526.2,541.2
XS Rating Curve= 0 ,0
Exp/Cntr=0.3,0.1

Type RM Length L Ch R = 1 ,5659    ,506.8,511.8,516.7
XS GIS Cut Line= 2
     1988381.525      173547.693        1988421.      172762.588
#Sta/Elev= 30
       0 1704.16    79.6 1672.11    89.6 1671.31   109.5 1663.01   119.4 1662.31
   149.3 1649.69   189.1 1635.17     199 1634.98     209  1632.7   238.8 1628.75
   268.7 1626.35     408 1625.43   423.7 1624.52   427.9 1624.29   438.7 1624.61
   447.8 1626.55   467.7 1633.26   477.6 1633.58   487.6 1636.36   517.4 1645.38
   567.2 1662.38   577.1 1663.06   587.1 1666.43   656.7 1696.91   666.7 1697.96
   676.6 1701.27   746.3 1730.27   756.2 1731.53   766.2 1734.52   786.1 1742.67
#Mann= 3 , 0 , 0
       0     .06       0   423.7    .045       0   438.7     .06       0
Bank Sta=423.7,438.7
XS Rating Curve= 0 ,0
Exp/Cntr=0.3,0.1

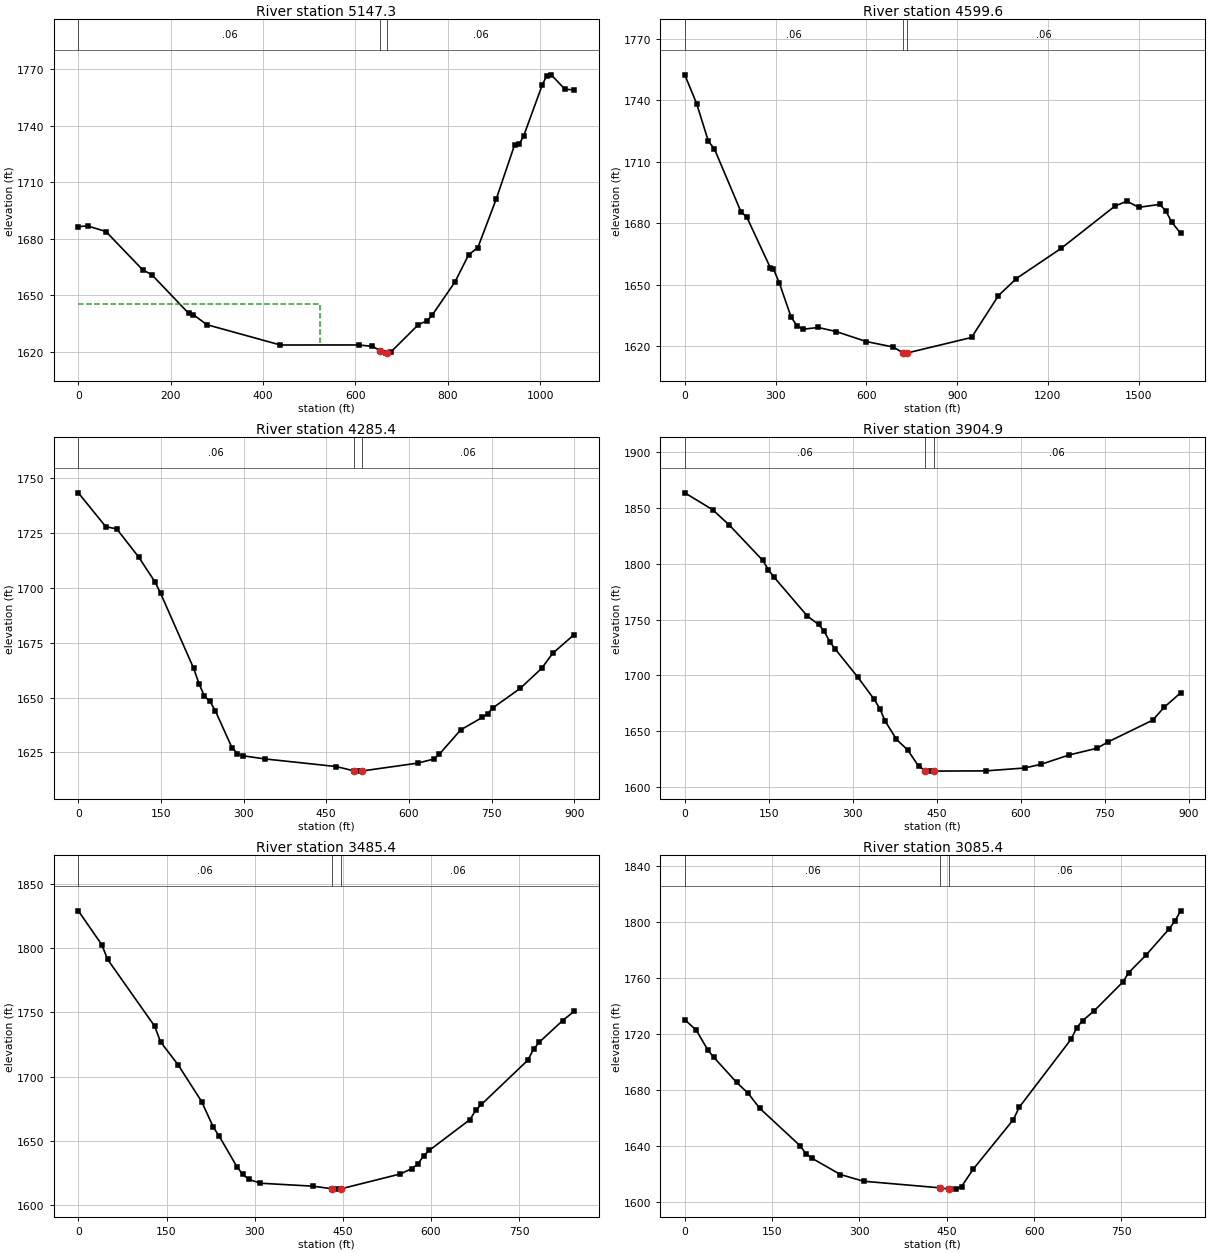
Type RM Length L Ch R = 1 ,5147.3  ,528.1,547.7,567.3
XS GIS Cut Line= 3
     1988712.075      173790.059     1988913.589      173113.371
      1989046.77      172770.909
#Sta/Elev= 30
       0  1686.5    19.9 1686.91    59.7 1683.92   139.2  1663.6   159.1 1660.99
   238.7 1640.54   248.6 1639.83   278.4 1634.45   437.6 1623.67   606.6  1623.7
   636.4 1622.96     654 1620.63   666.3 1619.36     669 1619.49   676.2 1619.85
   735.8 1634.39   755.7 1636.66   765.6 1639.35   815.3 1657.09   845.1 1671.59
     865 1675.41   904.7 1701.11   944.4 1729.81   954.3 1730.26   964.3 1734.72
    1004 1761.47  1013.9 1766.59  1023.8 1767.11  1053.6 1759.47  1073.5 1759.12
#Mann= 3 , 0 , 0
       0     .06       0     654    .045       0     669     .06       0
#XS Ineff= 2 , 0
           523.5 1645.55
Permanent Ineff=
       F       F
Bank Sta=654,669
XS Rating Curve= 0 ,0
Exp/Cntr=0.3,0.1

Type RM Length L Ch R = 1 ,4599.6  ,319.2,314.2,307.6
XS GIS Cut Line= 4
     1988804.125      173919.426     1988914.562      173585.725
     1989475.837        173332.3      1989552.96      172665.563
#Sta/Elev= 30
       0 1752.31    39.1 1738.27    78.1 1719.83    97.6 1716.26   185.5 1685.57
     205 1682.88   283.2 1658.07   292.9 1657.65   312.4 1650.82   351.5 1634.06
   371.4 1629.86   391.2 1628.26   440.9 1629.11   500.5 1627.11   599.8 1622.25
   689.2 1619.56   720.5 1616.74     729  1616.6   735.5  1616.7   947.5 1624.23
  1036.4 1644.63  1095.6 1652.96  1243.7 1667.69  1421.4  1688.3  1460.8 1690.69
  1500.3  1687.7  1569.4 1689.12  1589.2 1686.04  1608.9 1680.55  1638.5 1675.01
#Mann= 3 , 0 , 0
       0     .06       0   720.5    .045       0   735.5     .06       0
Bank Sta=720.5,735.5
XS Rating Curve= 0 ,0
Exp/Cntr=0.3,0.1

Type RM Length L Ch R = 1 ,4285.4  ,379.8,380.5,382.7
XS GIS Cut Line= 3
     1989034.983      173869.298     1989450.126      173576.822
     1989754.132      173329.111
#Sta/Elev= 30
       0 1743.46    49.8 1728.01    69.7    1727   109.5 1714.17   139.4 1702.71
   149.4 1697.58   209.1 1663.52   219.1 1656.39     229 1650.56     239 1648.34
   248.9  1643.9   278.8 1627.23   288.8 1624.53   298.7  1623.5   338.6 1622.07
     468 1618.59   500.3 1616.63   507.8  1616.5   515.3 1616.58   615.7 1620.14
   645.1 1621.99   654.9 1624.11   694.1 1635.33   733.3    1641   743.1 1642.75
   752.9 1645.44   801.9 1654.22   841.2 1663.42   860.8  1670.2     900 1678.78
#Mann= 3 , 0 , 0
       0     .06       0   500.3    .045       0   515.3     .06       0
Bank Sta=500.3,515.3
XS Rating Curve= 0 ,0
Exp/Cntr=0.3,0.1

Type RM Length L Ch R = 1 ,3904.9  ,413.9,419.5,424.8
XS GIS Cut Line= 2
     1989172.323      174140.842     1989908.411      173648.777
#Sta/Elev= 30
       0 1863.28    49.7 1848.18    79.6 1834.39   139.3  1802.8   149.2 1794.59
   159.2 1787.93   218.9 1753.08   238.8 1745.56   248.7 1739.73   258.7 1730.29
   268.6 1723.54   308.4 1698.82   338.2 1678.64   348.2 1670.31   358.1  1658.9
     378  1642.8   397.9 1633.38   417.8 1618.71   429.8 1614.98   437.7 1614.45
   444.8 1614.49   537.2 1614.67   606.9 1617.24   636.7 1620.64   686.4 1628.91
   736.2 1634.92   756.1 1640.64   835.7 1660.05   855.6 1671.36   885.4 1684.43
#Mann= 3 , 0 , 0
       0     .06       0   429.8    .045       0   444.8     .06       0
Bank Sta=429.8,444.8
XS Rating Curve= 0 ,0
Exp/Cntr=0.3,0.1

Type RM Length L Ch R = 1 ,3485.4  ,400,400,400.3
XS GIS Cut Line= 3
     1989424.142      174360.059     1989821.847      174173.256
     1990189.932      174006.478
#Sta/Elev= 30
       0 1828.97    39.9 1802.59    49.9 1791.12   129.8 1739.22   139.8 1727.05
   169.8 1709.11   209.7 1680.61   229.7 1660.55   239.7 1653.58   269.6    1630
   279.6  1623.9   289.6 1620.09   309.6 1617.03   399.4 1614.72   431.9 1612.68
   439.4 1612.43   446.9 1612.68   547.8 1624.24   567.5 1628.43   577.4 1631.91
   587.2 1638.19   597.1 1642.63   666.1 1666.49   675.9 1673.65   685.8 1678.37
   764.6 1712.72   774.5 1721.33   784.4 1726.86   823.8 1743.55   843.5 1750.81
#Mann= 3 , 0 , 0
       0     .06       0   431.9    .045       0   446.9     .06       0
Bank Sta=431.9,446.9
XS Rating Curve= 0 ,0
Exp/Cntr=0.3,0.1

Type RM Length L Ch R = 1 ,3085.4  ,553.1,538.5,522.8
XS GIS Cut Line= 3
     1989598.889      174679.233     1990000.429      174486.053
     1990370.822      174319.629
#Sta/Elev= 30
       0 1730.44    19.8    1723    39.6  1708.8    49.5 1703.76    89.1 1685.69
   108.9 1677.92   128.7 1667.24     198 1640.55   207.9 1634.89   217.8 1631.72
   267.4 1619.95     307 1615.18   438.1 1610.48   453.1 1609.65   455.5 1609.54
   465.4 1609.67   475.3 1611.34   495.1 1623.62   564.4 1659.17   574.3 1667.91
   663.5 1716.52   673.4  1724.9   683.3 1729.79   703.1 1736.79   752.6 1757.44
   762.5  1764.1   792.2 1776.57   831.8 1795.26   841.8 1800.81   851.7 1808.21
#Mann= 3 , 0 , 0
       0     .06       0   438.1    .045       0   453.1     .06       0
Bank Sta=438.1,453.1
XS Rating Curve= 0 ,0
Exp/Cntr=0.3,0.1

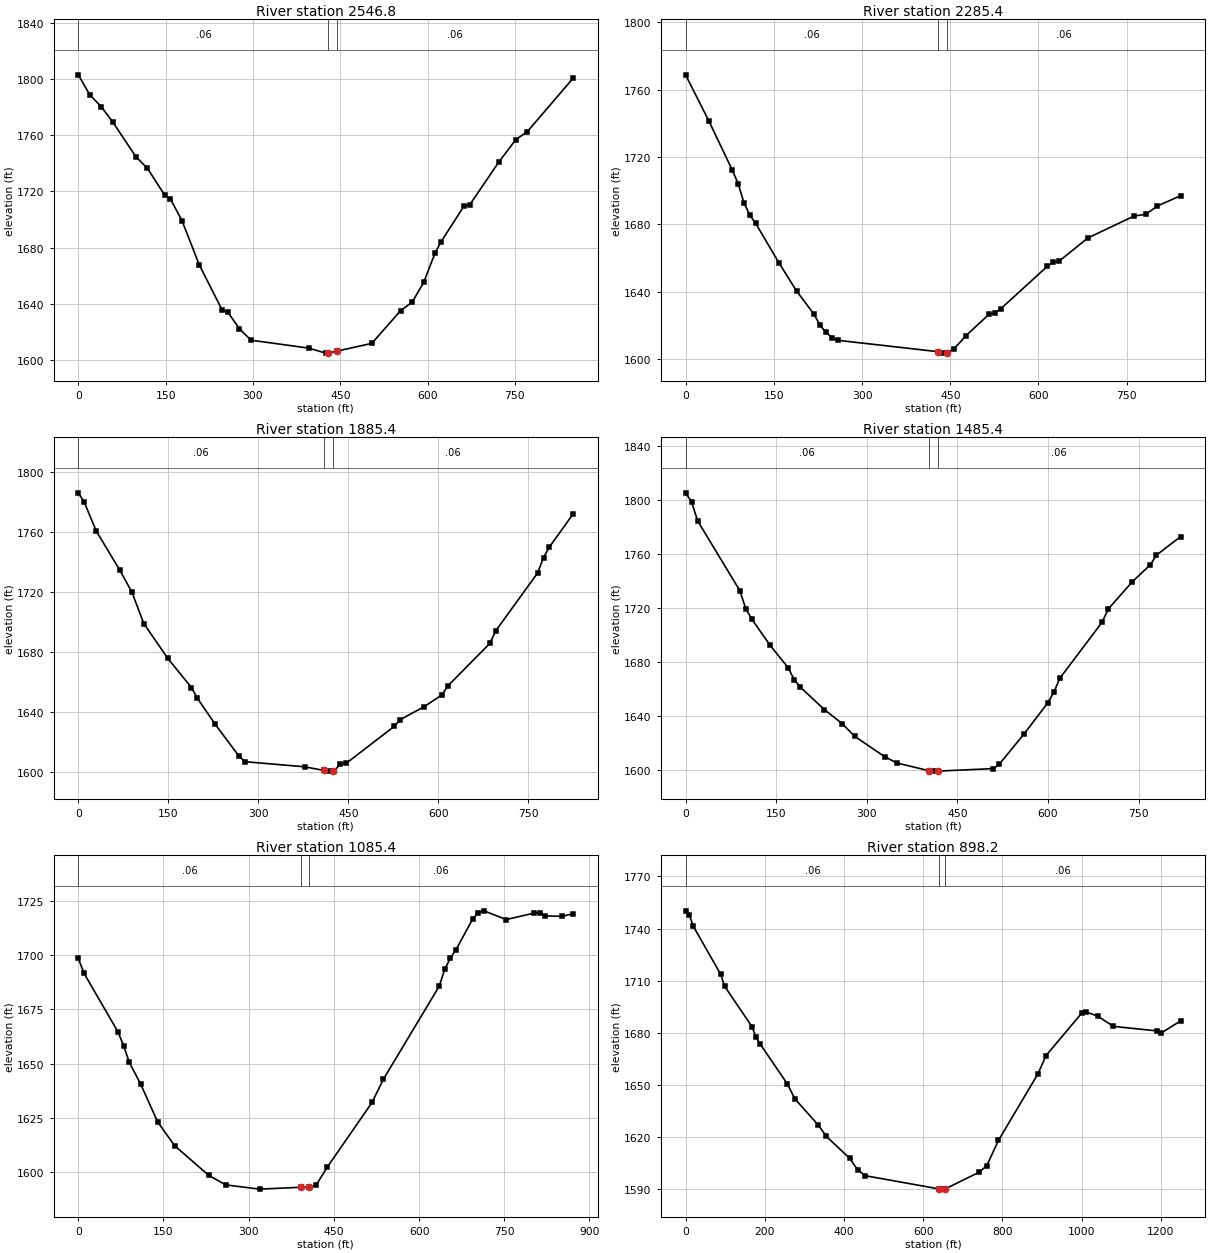
Type RM Length L Ch R = 1 ,2546.8  ,253.9,261.4,263.8
XS GIS Cut Line= 3
     1990107.186      175180.283     1990346.576      174703.091
     1990431.557      174398.199
#Sta/Elev= 30
       0 1802.86    19.8 1788.66    39.6 1780.14    59.3 1769.26    98.9  1744.7
   118.6 1736.52   148.3 1717.49   158.2 1714.69     178 1699.34   207.6 1668.04
   247.2 1635.66     257 1634.11   276.8 1622.51   296.6 1614.35   395.5 1608.74
   425.1 1605.16   429.7 1605.36   444.7 1606.62   504.2  1612.1   553.6 1635.35
   573.4 1641.32   593.2 1655.37     613 1676.47   622.9 1684.14   662.5 1709.66
   672.4 1710.52   721.8 1740.63   751.5 1756.86   771.3 1762.52   850.4 1800.72
#Mann= 3 , 0 , 0
       0     .06       0   429.7    .045       0   444.7     .06       0
Bank Sta=429.7,444.7
XS Rating Curve= 0 ,0
Exp/Cntr=0.3,0.1

Type RM Length L Ch R = 1 ,2285.4  ,385.5,400,422.9
XS GIS Cut Line= 3
     1990207.691      175236.905     1990516.483      174927.274
     1990730.045      174583.838
#Sta/Elev= 30
       0  1768.8    39.8 1741.28    79.5  1712.2    89.4 1704.15    99.4 1692.69
   109.3 1685.38   119.3 1680.55     159 1657.01   188.8 1640.41   218.6 1626.52
   228.6 1620.01   238.5 1616.03   248.5 1612.78   258.4 1611.17   429.8 1604.38
   437.3 1603.54   444.8 1603.55     457 1606.26   476.8 1613.96   516.2 1626.69
   526.1 1627.46   535.9 1629.87   614.8 1655.03   624.7  1657.5   634.6 1658.02
   683.9 1671.92   762.8    1685   782.5 1685.96   802.3 1690.95   841.7 1697.02
#Mann= 3 , 0 , 0
       0     .06       0   429.8    .045       0   444.8     .06       0
Bank Sta=429.8,444.8
XS Rating Curve= 0 ,0
Exp/Cntr=0.3,0.1

Type RM Length L Ch R = 1 ,1885.4  ,400,400,396.5
XS GIS Cut Line= 3
     1990255.465      175340.317     1990668.472      175283.014
     1991076.625      175278.037
#Sta/Elev= 30
       0 1786.23     9.9 1780.01    29.8 1760.79    69.5  1734.4    89.4 1719.88
   109.2 1698.96   148.9 1675.86   188.6 1656.24   198.6 1649.04   228.3 1631.62
     268 1610.34     278 1606.73   377.2 1603.34   409.5 1600.87     417 1600.44
   424.5 1600.62   426.9 1600.68   436.9 1605.36   446.8 1605.74   526.5  1630.3
   536.4 1634.79   576.2  1643.4   606.1 1651.34   616.1 1657.39   685.8 1685.66
   695.7 1694.06   765.4 1732.62   775.4 1743.02   785.3 1750.13   825.2 1772.38
#Mann= 3 , 0 , 0
       0     .06       0   409.5    .045       0   424.5     .06       0
Bank Sta=409.5,424.5
XS Rating Curve= 0 ,0
Exp/Cntr=0.3,0.1

Type RM Length L Ch R = 1 ,1485.4  ,396.5,400,386.4
XS GIS Cut Line= 3
     1990259.044      175734.932     1990664.878      175678.577
     1991069.059      175610.508
#Sta/Elev= 30
       0 1805.44      10 1798.68      20 1784.65    89.9 1732.83    99.9 1719.23
   109.9 1711.62   139.9 1692.37   169.9 1675.63   179.9  1666.8   189.9 1661.34
   229.8 1644.64   259.8 1633.99   279.8 1624.85   329.8 1609.64   349.8 1605.02
   402.2 1599.36   409.7 1598.98   417.2 1598.98   509.7 1600.86   519.7 1604.31
   559.7 1626.18   599.7 1649.67   609.7 1657.53   619.7 1667.98   689.6 1709.47
   699.6  1719.2   739.6 1739.47   769.6 1752.15   779.6 1759.25   819.6 1773.01
#Mann= 3 , 0 , 0
       0     .06       0   402.2    .045       0   417.2     .06       0
Bank Sta=402.2,417.2
XS Rating Curve= 0 ,0
Exp/Cntr=0.3,0.1

Type RM Length L Ch R = 1 ,1085.4  ,188.7,187.1,203.3
XS GIS Cut Line= 3
     1990353.024      176055.476      1990751.98       176062.12
     1991124.851      175771.586
#Sta/Elev= 30
       0 1698.55      10 1691.67    69.8 1664.69    79.8  1658.3    89.8 1650.61
   109.7 1640.69   139.6 1623.23   169.6 1612.23   229.4 1598.62   259.4 1594.19
   319.2 1592.23   391.5 1593.08   406.5 1593.12   418.7 1594.04   438.4 1602.38
   517.2 1632.16   536.9 1642.73   635.4 1685.68   645.2 1693.48   655.1  1698.7
   664.9 1702.48   694.4 1716.65   704.3 1719.62   714.1 1720.42   753.5 1716.41
   802.8 1719.39   812.6 1719.55   822.5 1718.08     852 1717.88   871.7 1719.11
#Mann= 3 , 0 , 0
       0     .06       0   391.5    .045       0   406.5     .06       0
Bank Sta=391.5,406.5
XS Rating Curve= 0 ,0
Exp/Cntr=0.3,0.1

Type RM Length L Ch R = 1 ,898.2   ,406.9,378.9,349.9
XS GIS Cut Line= 3
     1990090.081      176283.291     1990839.001      176242.441
     1991151.228      175852.068
#Sta/Elev= 30
       0 1750.17     9.9 1747.58    19.7 1741.24    88.8 1713.65    98.7 1706.78
   167.8 1683.55   177.6 1677.57   187.5 1673.86   256.6 1650.79   276.3    1642
   335.5  1626.9   355.3 1620.53   414.5 1607.86   434.2 1601.31     454 1597.88
   640.5 1590.27   651.3 1590.18   655.5 1590.31   740.2 1599.78     760 1603.52
     790  1618.2     890 1656.62     910 1666.95    1000 1691.33    1010 1692.07
    1040 1689.72    1080 1683.74  1189.9 1681.15  1199.9 1679.79  1249.9 1686.92
#Mann= 3 , 0 , 0
       0     .06       0   640.5    .045       0   655.5     .06       0
Bank Sta=640.5,655.5
XS Rating Curve= 0 ,0
Exp/Cntr=0.3,0.1

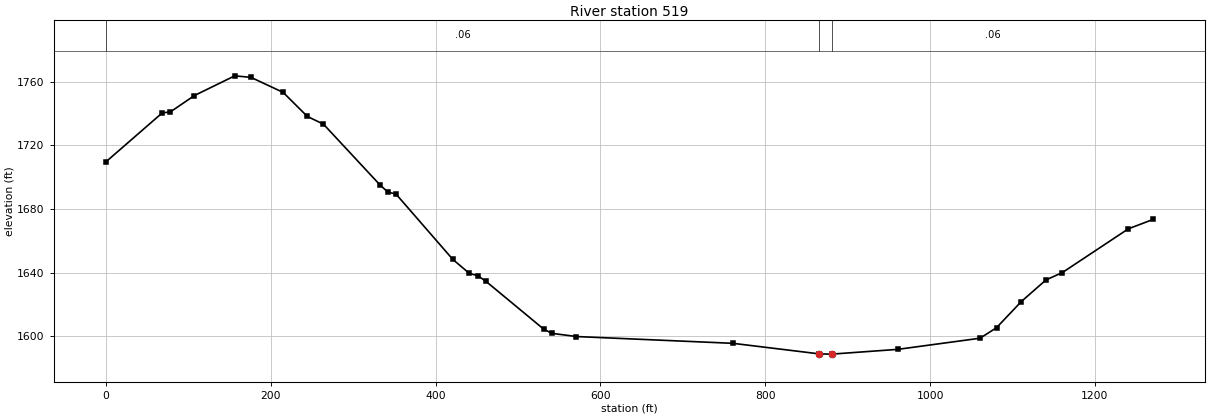
Type RM Length L Ch R = 1 ,519     ,326.4,302.7,278.9
XS GIS Cut Line= 3
     1990713.046      177389.649     1990721.558      176998.711
     1990988.785       176160.74
#Sta/Elev= 30
       0 1709.68    68.4 1740.47    78.2 1741.08   107.5  1751.4   156.4 1763.77
     176  1762.8   215.1 1753.35   244.4 1738.24     264 1733.37   332.4 1695.28
   342.2 1690.62   351.9  1689.5     421 1648.32     441 1639.57     451 1638.16
     461 1634.64     531 1604.61     541 1601.88   570.9 1599.87   760.8  1595.6
   865.7 1588.96   880.7 1588.81   960.7  1591.8  1060.7 1598.81  1080.7 1605.45
  1110.7 1621.84  1140.6 1635.43  1160.6  1640.1  1240.6 1667.58  1270.6 1673.48
#Mann= 3 , 0 , 0
       0     .06       0   865.7    .045       0   880.7     .06       0
Bank Sta=865.7,880.7
XS Rating Curve= 0 ,0
Exp/Cntr=0.3,0.1