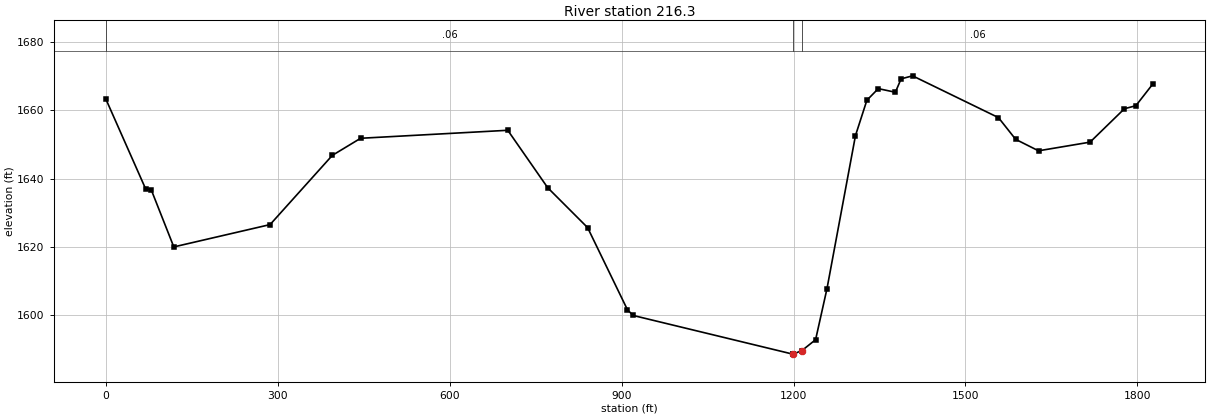
HEC-RAS study LckCrk.prj: LckCrk

--- LckCrk.g01 (geometry) --- (continued)

Type RM Length L Ch R = 1 ,216.3   ,209.3,216.3,223.3
XS GIS Cut Line= 4
     1991349.628      177478.157     1991444.027       176783.21
     1991016.018      176259.462     1991220.137      175858.776
#Sta/Elev= 30
       0 1663.28    69.2 1637.05      79 1636.79   118.5    1620   286.5 1626.54
   395.1 1646.81   444.5 1651.82   701.3 1654.16     771 1637.34   840.6 1625.66
   910.2 1601.58   920.2 1599.92  1198.7  1588.6  1199.4 1588.63  1214.4 1589.61
  1238.5 1592.83  1258.4  1607.8  1308.1 1652.62    1328 1662.96  1347.9 1666.36
  1377.7  1665.3  1387.7 1669.22  1407.7 1670.11  1557.6 1657.87  1587.6 1651.51
  1627.5 1648.15  1717.5 1650.69  1777.4 1660.47  1797.4 1661.36  1827.4 1667.81
#Mann= 3 , 0 , 0
       0     .06       0  1199.4    .045       0  1214.4     .06       0
Bank Sta=1199.4,1214.4
XS Rating Curve= 0 ,0
Exp/Cntr=0.3,0.1

Chan Stop Cuts=-1
Use User Specified Reach Order=0
Composite Channel Slope=5